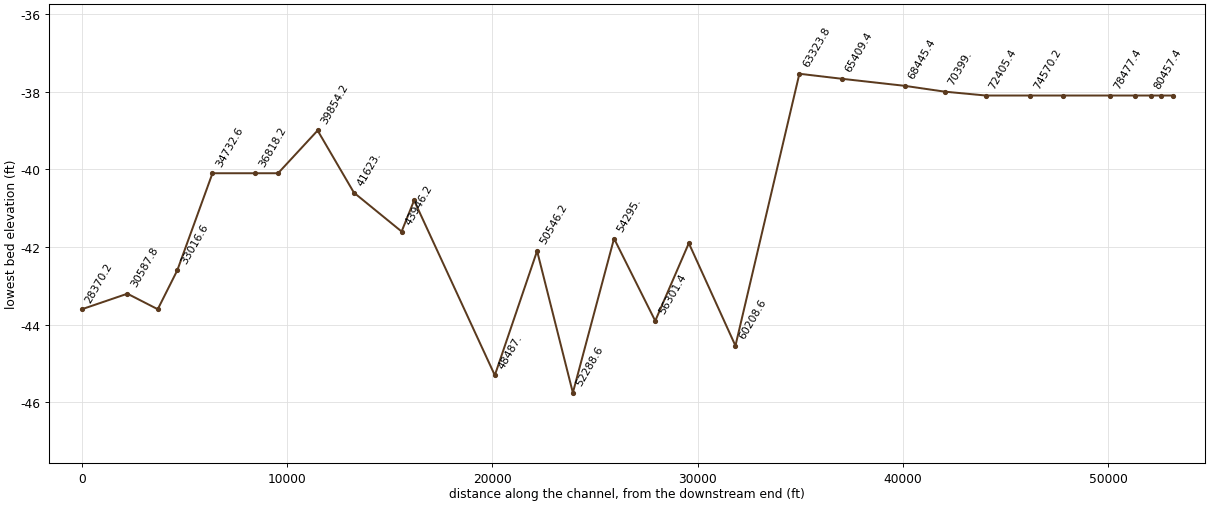
--- G100-00-00.prj (project) ---

Proj Title=G100-00-00
Current Plan=p03
Default Exp/Contr=.3,.1
English Units
Geom File=g01
Geom File=g02
Flow File=f03
Flow File=f04
Plan File=p03
Plan File=p04
Y Axis Title=Elevation
X Axis Title(PF)=Main Channel Distance
X Axis Title(XS)=Station
BEGIN DESCRIPTION:
Buffalo Bayou
(Lower) Buffalo Bayou (Houston Ship Channel)
HCFCD Unit G100-00-00
Flood Hazard Model
10, 2, 1, 0.2% Event
Filename G100_00_00.prj
Prepared by: Matthew Fischer Date: 6-30-04
Reviewd by:		Date:
Status Final Submittal
END DESCRIPTION:
DSS Export Rating Curves= 0
DSS Export Rating Curve Sorted= 0
DSS Export Volume Flow Curves= 0
DXF OffsetX= 0
DXF OffsetY= 0
DXF ScaleX= 1
DXF ScaleY= 10

--- G100-00-00.p03 (plan) ---

Plan Title=FEMA Effective June 2007
Version=Version 3.0.1  Mar 2001
Short Identifier=FEMAeff0607
Geom File=g01
Flow File=f03
Subcritical Flow
K Sum by GR= 0
Std Step Tol= 0.01
Critical Tol= 0.01
Num of Std Step Trials= 20
Max Error Tol= 0.3
Flow Tol Ratio= 0.001
Split Flow NTrial= 30
Split Flow Tol= 0.02
Split Flow Ratio= 0.02
Log Output Level= 0
Friction Slope Method= 0
Unsteady Friction Slope Method= 2
Secant Critical Depth
Global Vel Dist= 0 , 0 , 0
Global Log Level= 0
CheckData=True
Encroach Param=-1 ,0,0, 0
Computation Interval=1HOUR
Output Interval=1HOUR
Run HTab= 0
Run UNet= 0
Run PostProcess= 0
UNET Theta= 1
UNET ZTol= 0.02
UNET ZSATol= 0.1
UNET MxIter= 20
UNET MaxInSteps= 20
UNET DtIC= 0
UNET DtMin= 0
UNET MaxCRTS= 20
UNET WFStab= 2
UNET SFStab= 1
UNET WFX= 1
UNET SFX= 1
UNET Convert EG Bridges=-1
UNET Use Existing IB Tables=-1
Instantaneous Interval=1HOUR
Write IC File= 0
Write Velocity= 0
Write Detailed= 0

--- G100-00-00.p04 (plan) ---

Plan Title=Floodway
Version=Version 3.0.1  Mar 2001
Short Identifier=Floodway0607
Geom File=g02
Flow File=f04
Subcritical Flow
K Sum by GR= 0
Std Step Tol= 0.01
Critical Tol= 0.01
Num of Std Step Trials= 20
Max Error Tol= 0.3
Flow Tol Ratio= 0.001
Split Flow NTrial= 30
Split Flow Tol= 0.02
Split Flow Ratio= 0.02
Log Output Level= 0
Friction Slope Method= 0
Unsteady Friction Slope Method= 2
Secant Critical Depth
Global Vel Dist= 0 , 0 , 0
Global Log Level= 0
CheckData=True
Encroach Param=-1 ,0,0, 2
Encroach River=G100-00-00
Encroach Reach=Main
Encroach Node=81510.
       1 1111.71 1527.38
Encroach Node=80959.
       1 1111.71 1527.38
Encroach Node=80457.4
       1  1305.5 1791.29
Encroach Node=79691.8
       1 1309.45 1856.28
Encroach Node=78477.4
       1  1746.5 2285.96
Encroach Node=76180.6
       1 1423.88 1990.04
Encroach Node=74570.2
       1 1177.76 1854.41
Encroach Node=72405.4
       1 1237.37 2303.05
Encroach Node=70399.
       1 1745.65 2483.65
Encroach Node=68445.4
       1  1031.1 1828.67
Encroach Node=65409.4
       1 1326.56 1979.41
Encroach Node=63323.8
       1 1613.98 2235.94
Encroach Node=60208.6
       1 1606.74  3101.3
Encroach Node=57938.2
       1 1317.76 2133.21
Encroach Node=56301.4
       1   932.6 1625.88
Encroach Node=54295.
       1 1380.79 2051.49
Encroach Node=52288.6
       1 1726.68 2491.52
Encroach Node=50546.2
       1 2163.05  2918.2
Encroach Node=48487.
       1 1925.05 2986.92
Encroach Node=44553.4
       1       0 1343.61
Encroach Node=43946.2
       1 1460.72 2332.79
Encroach Node=41623.
       1 1515.26 2217.53
Encroach Node=39854.2
       1 1019.47 1885.01
Encroach Node=37927.
       1 1572.47 2877.97
Encroach Node=36818.2
       1  968.14 1615.99
Encroach Node=34732.6
       1  776.91 1851.98
Encroach Node=33016.6
       1 1315.49 2561.27
Encroach Node=32066.2
       1  949.24 2596.65
Encroach Node=30587.8
       1       0 1647.66
Encroach Node=28370.2
       1  943.28 2177.22
Encroach Node=26812.6
       1  267.24 1900.39
Encroach Node=24885.4
       1  504.98 2000.11
Encroach Node=22800.2
       1 -149.55 1598.16
Encroach Node=20846.2
       1  982.13 2401.63
Encroach Node=16859.8
       1   757.3 1960.19
Encroach Node=15962.2
       1  115.88 1363.93
Encroach Node=13955.8
       1  627.48  2057.7
Encroach Node=11315.8
       1  513.98 1750.63
Encroach Node=10893.4
       1 1215.66  2316.1
Encroach Node=7936.6
       1  315.03 1768.95
Encroach Node=6352.6
       1 1319.67 2937.87
Encroach Node=4451.8
       1 -132.59 1711.79
Encroach Node=3184.6
       1 -263.51 2104.33
Encroach Node=1415.8
       1       0    2575
Encroach Node=703.
       1  428.82 2941.53
Encroach Reach=G100-00-00_0007
Encroach Node=81510.
       1 1111.71 1527.38
Encroach Node=80959.
       1 1111.71 1527.38
Encroach Node=80457.4
       1  1305.5 1791.29
Encroach Node=79691.8
       1 1309.45 1856.28
Encroach Node=78477.4
       1  1746.5 2285.96
Encroach Node=76180.6
       1 1423.88 1990.04
Encroach Node=74570.2
       1 1177.76 1854.41
Encroach Node=72405.4
       1 1237.37 2303.05
Encroach Node=70399.
       1 1745.65 2483.65
Encroach Node=68445.4
       1  1031.1 1828.67
Encroach Node=65409.4
       1 1326.56 1979.41
Encroach Node=63323.8
       1 1613.98 2235.94
Encroach Node=60208.6
       1 1606.74  3101.3
Encroach Node=57938.2
       1 1317.76 2133.21
Encroach Node=56301.4
       1   932.6 1625.88
Encroach Node=54295.
       1 1380.79 2051.49
Encroach Node=52288.6
       1 1726.68 2491.52
Encroach Node=50546.2
       1 2163.05  2918.2
Encroach Node=48487.
       1 1925.05 2986.92
Encroach Node=44553.4
       1       0 1343.61
Encroach Node=43946.2
       1 1460.72 2332.79
Encroach Node=41623.
       1 1515.26 2217.53
Encroach Node=39854.2
       1 1019.47 1885.01
Encroach Node=37927.
       1 1572.47 2877.97
Encroach Node=36818.2
       1  968.14 1615.99
Encroach Node=34732.6
       1  776.91 1851.98
Encroach Node=33016.6
       1 1315.49 2561.27
Encroach Node=32066.2
       1  949.24 2596.65
Encroach Node=30587.8
       1       0 1647.66
Encroach Node=28370.2
       1  943.28 2177.22
Encroach Node=26812.6
       1  267.24 1900.39
Encroach Node=24885.4
       1  504.98 2000.11
Encroach Node=22800.2
       1 -149.55 1598.16
Encroach Node=20846.2
       1  982.13 2401.63
Encroach Node=16859.8
       1   757.3 1960.19
Encroach Node=15962.2
       1  115.88 1363.93
Encroach Node=13955.8
       1  627.48  2057.7
Encroach Node=11315.8
       1  513.98 1750.63
Encroach Node=10893.4
       1 1215.66  2316.1
Encroach Node=7936.6
       1  315.03 1768.95
Encroach Node=6352.6
       1 1319.67 2937.87
Encroach Node=4451.8
       1 -132.59 1711.79
Encroach Node=3184.6
       1 -263.51 2104.33
Encroach Node=1415.8
       1       0    2575
Encroach Node=703.
       1  428.82 2941.53
Computation Interval=1HOUR
Output Interval=1HOUR
Run HTab= 0
Run UNet= 0
Run PostProcess= 0
UNET Theta= 1
UNET ZTol= 0.02
UNET ZSATol= 0.1
UNET MxIter= 20
UNET MaxInSteps= 20
UNET DtIC= 0
UNET DtMin= 0
UNET MaxCRTS= 20
UNET WFStab= 2
UNET SFStab= 1
UNET WFX= 1
UNET SFX= 1
UNET Convert EG Bridges=-1
UNET Use Existing IB Tables=-1
Instantaneous Interval=1HOUR
Write IC File= 0
Write Velocity= 0
Write Detailed= 0

--- G100-00-00.f03 (steady flow) ---

Flow Title=FEMA Effective June 2007
Version=Version 3.0.1  Mar 2001
Number of Profiles= 4
Profile Names=10PCT_10yr, 2PCT_50yr, 1PCT_100yr, 0.2PCT_500yr
River Rch & RM=Buffalo Bayou,G100-00-00      ,81153.6
   33393   54630   65302   94411
River Rch & RM=Buffalo Bayou,G100-00-00      ,80625.6
   33393   54630   65302   94411
River Rch & RM=Buffalo Bayou,G100-00-00      ,72072
   46739   77725   93558  137441
River Rch & RM=Buffalo Bayou,G100-00-00      ,62990.4
   55215   92568  111809  165559
River Rch & RM=Buffalo Bayou,G100-00-00      ,53961.6
   56812   95378  115272  170919
River Rch & RM=Buffalo Bayou,G100-00-00      ,44220
   59769  100590  121698  180882
River Rch & RM=Buffalo Bayou,G100-00-00      ,39520.8
   59974  100953  122146  181578
River Rch & RM=Buffalo Bayou,G100-00-00      ,31732.8
   76904  131026  159352  239701
River Rch & RM=Buffalo Bayou,G100-00-00      ,22308
   77447  131996  160555  241591
River Rch & RM=Buffalo Bayou,G100-00-00      ,13622.4
   78103  133169  162010  243879
River Rch & RM=Buffalo Bayou,G100-00-00      ,7603.2
   80428  137328  167172  252000
River Rch & RM=G100-00-00,G100-00-00_0007            ,81510.
   33393   54630   65302   94411
River Rch & RM=G100-00-00,G100-00-00_0007            ,80959.
   33393   54630   65302   94411
River Rch & RM=G100-00-00,G100-00-00_0007            ,72405.4
   46739   77725   93558  137441
River Rch & RM=G100-00-00,G100-00-00_0007            ,63323.8
   55215   92568  111809  165559
River Rch & RM=G100-00-00,G100-00-00_0007            ,54295.
   56812   95378  115272  170919
River Rch & RM=G100-00-00,G100-00-00_0007            ,44553.4
   59769  100590  121698  180882
River Rch & RM=G100-00-00,G100-00-00_0007            ,39854.2
   59974  100953  122146  181578
River Rch & RM=G100-00-00,G100-00-00_0007            ,32066.2
   76904  131026  159352  239701
River Rch & RM=G100-00-00,G100-00-00_0007            ,22800.2
   77447  131996  160555  241591
River Rch & RM=G100-00-00,G100-00-00_0007            ,13955.8
   78103  133169  162010  243879
River Rch & RM=G100-00-00,G100-00-00_0007            ,7936.6
   80428  137328  167172  252000
Boundary for River Rch & Prof#=G100-00-00,G100-00-00_0007            , 1
Up Type= 0
Dn Type= 1
Dn Known WS=1
Boundary for River Rch & Prof#=G100-00-00,G100-00-00_0007            , 2
Up Type= 0
Dn Type= 1
Dn Known WS=1
Boundary for River Rch & Prof#=G100-00-00,G100-00-00_0007            , 3
Up Type= 0
Dn Type= 1
Dn Known WS=1
Boundary for River Rch & Prof#=G100-00-00,G100-00-00_0007            , 4
Up Type= 0
Dn Type= 1
Dn Known WS=1
DSS Import GetInterval= 0
DSS Import GetPeak= 0
DSS Import FillOption= 0

--- G100-00-00.f04 (steady flow) ---

Flow Title=Floodway
Version=Version 3.0.1  Mar 2001
Number of Profiles= 2
Profile Names=1PCT_100yr, 1PCTFloodway_100yrFW
River Rch & RM=G100-00-00,G100-00-00_0007            ,81510.
   65302   65302
River Rch & RM=G100-00-00,G100-00-00_0007            ,80959.
   65302   65302
River Rch & RM=G100-00-00,G100-00-00_0007            ,72405.4
   93558   93558
River Rch & RM=G100-00-00,G100-00-00_0007            ,63323.8
  111809  111809
River Rch & RM=G100-00-00,G100-00-00_0007            ,54295.
  115272  115272
River Rch & RM=G100-00-00,G100-00-00_0007            ,44553.4
  121698  121698
River Rch & RM=G100-00-00,G100-00-00_0007            ,39854.2
  122146  122146
River Rch & RM=G100-00-00,G100-00-00_0007            ,32066.2
  159352  159352
River Rch & RM=G100-00-00,G100-00-00_0007            ,22800.2
  160555  160555
River Rch & RM=G100-00-00,G100-00-00_0007            ,13955.8
  162010  162010
River Rch & RM=G100-00-00,G100-00-00_0007            ,7936.6
  167172  167172
Boundary for River Rch & Prof#=G100-00-00,G100-00-00_0007            , 1
Up Type= 0
Dn Type= 1
Dn Known WS=1
Boundary for River Rch & Prof#=G100-00-00,G100-00-00_0007            , 2
Up Type= 0
Dn Type= 1
Dn Known WS=2
DSS Import GetInterval= 0
DSS Import GetPeak= 0
DSS Import FillOption= 0

--- G100-00-00.g01 (geometry) ---

Geom Title=G100-00-00 June 2007
Version=Version 3.0.1  Mar 2001

River Reach=G100-00-00      ,G100-00-00_0007
Reach XY= 30
     3146789.425     13838053.31     3149017.638     13834789.71
     3150257.572     13831444.23     3151146.581     13830297.87
     3152690.649     13829923.56     3156527.424     13830859.35
     3159288.031     13828671.92     3160808.704     13828087.05
     3162212.403     13828566.65     3163967.026     13830005.44
     3166060.876     13830812.56      3168692.81     13830321.27
     3170611.198       13831105.     3171605.484     13832239.66
     3172938.998     13835421.37     3173558.965     13836099.83
     3176225.992     13837550.32     3178425.119     13838263.86
     3183642.198     13838954.01      3185771.14     13838041.61
     3189163.412     13835386.28     3195971.349     13834906.68
     3198767.048     13835210.82     3201621.235     13836977.14
     3203001.538     13837257.88     3203972.429     13837936.33
     3207294.515     13841562.55     3208803.491     13845048.41
     3209762.685     13845914.02  3211096.029997  13846157.29085

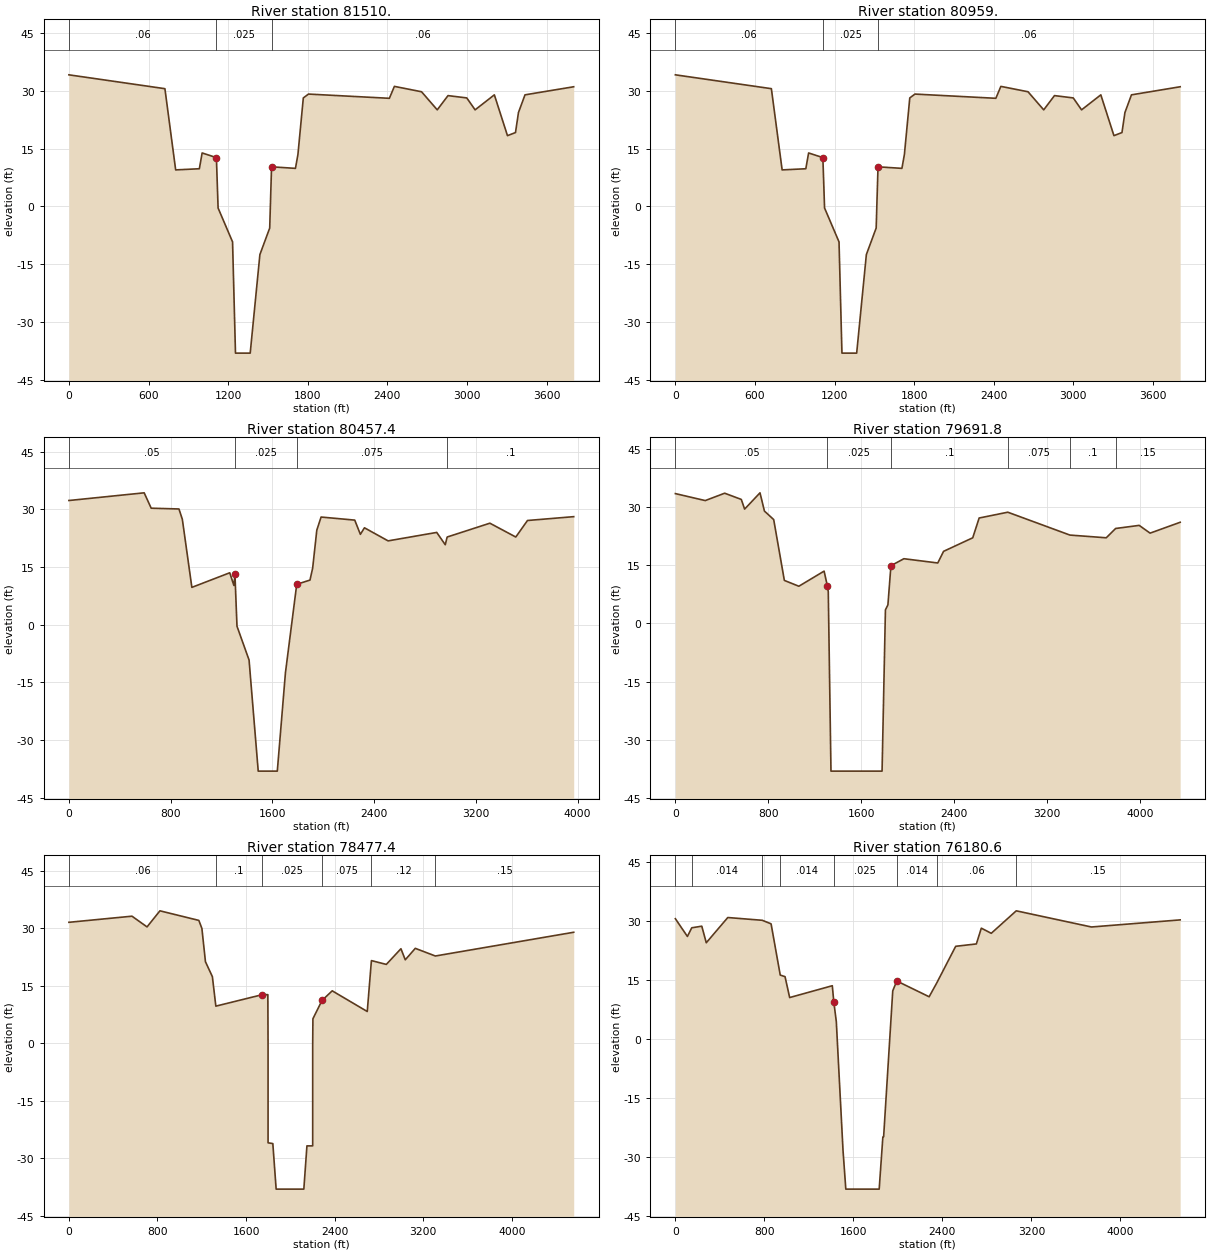
Type RM Length L Ch R = 1 ,81510.  ,551,551,551
BEGIN DESCRIPTION:
Added cross section to match the upper limit of the existing study
END DESCRIPTION:
#Sta/Elev= 30
       0    34.2   723.6    30.6  804.73     9.5   983.2     9.8 1004.22    13.9
 1111.71    12.7  1124.5     -.4  1233.5    -9.2  1255.5   -38.1  1366.5   -38.1
  1439.5   -12.5  1513.5    -5.6 1527.38    10.3 1707.51     9.9 1726.19    13.5
 1766.81    28.2 1805.86    29.2 2415.44    28.1 2453.33    31.2 2657.97    29.8
 2776.26    25.1 2857.44    28.8 2998.82    28.2 3061.61    25.1  3206.7      29
 3305.59    18.4 3366.03    19.2 3388.41    24.4 3437.68      29  3804.8    31.1
#Mann= 3 ,-1 , 0
       0     .06       0 1111.71    .025       0 1527.38     .06       0
#Block Obstruct= 2 , 0
         1007.93   13.87
Bank Sta=1111.71,1527.38
XS Rating Curve= 0
Exp/Cntr=.3,.1

Type RM Length L Ch R = 1 ,80959.  ,160,501.6,580
#Sta/Elev= 30
       0    34.2   723.6    30.6  804.73     9.5   983.2     9.8 1004.22    13.9
 1111.71    12.7  1124.5     -.4  1233.5    -9.2  1255.5   -38.1  1366.5   -38.1
  1439.5   -12.5  1513.5    -5.6 1527.38    10.3 1707.51     9.9 1726.19    13.5
 1766.81    28.2 1805.86    29.2 2415.44    28.1 2453.33    31.2 2657.97    29.8
 2776.26    25.1 2857.44    28.8 2998.82    28.2 3061.61    25.1  3206.7      29
 3305.59    18.4 3366.03    19.2 3388.41    24.4 3437.68      29  3804.8    31.1
#Mann= 3 ,-1 , 0
       0     .06       0 1111.71    .025       0 1527.38     .06       0
#Block Obstruct= 2 , 0
         1011.45   13.87
Bank Sta=1111.71,1527.38
XS Rating Curve= 0
Exp/Cntr=.3,.1

Type RM Length L Ch R = 1 ,80457.4 ,1600,765.6,480
#Sta/Elev= 30
       0    32.3  591.78    34.3  647.08    30.3   865.3    30.1  891.91    27.4
  966.72     9.7 1264.57    13.5 1297.39    10.2  1305.5    13.1  1321.5     -.4
  1416.5    -9.2  1488.5   -38.1  1638.5   -38.1  1702.5   -12.5 1791.29    10.5
 1895.43    11.6 1916.38    14.7 1949.15    24.6 1982.73      28 2247.35    27.2
 2291.65    23.5 2323.75    25.2 2509.68    21.8 2891.91      24    2959    20.8
 2973.94    22.8 3309.84    26.4 3513.53    22.8 3605.49    27.1 3968.92    28.1
#Mann= 4 ,-1 , 0
       0     .05       0  1305.5    .025       0 1791.29    .075       0
 2973.94      .1       0
Bank Sta=1305.5,1791.29
XS Rating Curve= 0
Exp/Cntr=.3,.1

Type RM Length L Ch R = 1 ,79691.8 ,4800,1214.4,640
#Sta/Elev= 30
       0    33.5  257.18    31.7  424.53    33.6  567.77      32  596.32    29.5
  728.79    33.7  766.92      29  846.74    26.8  938.61    11.1 1063.41     9.6
 1280.89    13.5 1309.45     9.6 1316.76     8.2    1340   -38.1    1780   -38.1
 1808.95     3.5 1830.37     4.8 1856.28    14.9 1968.11    16.7 2259.72    15.6
 2309.52    18.6 2560.84    22.1 2616.01    27.2 2862.54    28.7 3397.74    22.8
 3710.54    22.1 3791.39    24.5 3994.12    25.3 4088.21    23.3 4347.18    26.1
#Mann= 6 ,-1 , 0
       0     .05       0 1309.45    .025       0 1856.28      .1       0
 2862.54    .075       0 3397.74      .1       0 3791.39     .15       0
Bank Sta=1309.45,1856.28
XS Rating Curve= 0
Exp/Cntr=.3,.1

Type RM Length L Ch R = 1 ,78477.4 ,2160,2296.8,2200
#Sta/Elev= 30
       0    31.6  569.62    33.2  705.58    30.4  822.04    34.6 1173.29    32.1
    1201      30 1233.09    21.3 1295.67    17.4 1326.87     9.7  1746.5    12.7
  1796.5    12.7  1798.5     -.5  1798.5     -26  1841.5   -26.2  1871.5   -38.1
  2121.5   -38.1  2149.5   -26.8  2201.5   -26.8  2201.5     -.5  2203.5     6.4
 2285.96    11.2 2377.89    13.7 2694.19     8.3 2731.79    21.6 2866.42    20.6
 2998.41    24.7 3037.48    21.8 3128.05    24.8 3309.19    22.8 4558.57      29
#Mann= 6 ,-1 , 0
       0     .06       0 1326.87      .1       0  1746.5    .025       0
 2285.96    .075       0 2731.79     .12       0 3309.19     .15       0
#Block Obstruct= 2 , 0
                         2566.96            9.82
Bank Sta=1746.5,2285.96
XS Rating Curve= 0
Exp/Cntr=.3,.1

Type RM Length L Ch R = 1 ,76180.6 ,1680,1610.4,1400
#Sta/Elev= 30
       0    30.5  108.21      26  147.31    28.2  237.47    28.6  277.78    24.4
   471.2    30.8  780.57    30.1  860.35    29.2  942.63    16.2  985.77    15.8
 1027.32    10.5 1410.72    13.5 1423.88   9.446 1446.63     4.4    1507   -28.3
    1532   -38.1    1832   -38.1    1865   -24.9    1872   -24.8    1954    12.2
 1990.04    14.7 2281.07    10.7 2349.37    14.2 2519.63    23.5 2705.61    24.1
 2750.01    28.1  2839.5    26.8 3064.06    32.5 3740.06    28.4 4537.47    30.2
#Mann= 8 ,-1 , 0
       0      .1       0  147.31    .014       0  780.57     .06       0
  942.63    .014       0 1423.88    .025       0 1990.04    .014       0
 2349.37     .06       0 3064.06     .15       0
#Block Obstruct= 2 , 0
                         2052.86            14.6
Bank Sta=1423.88,1990.04
XS Rating Curve= 0
Exp/Cntr=.3,.1

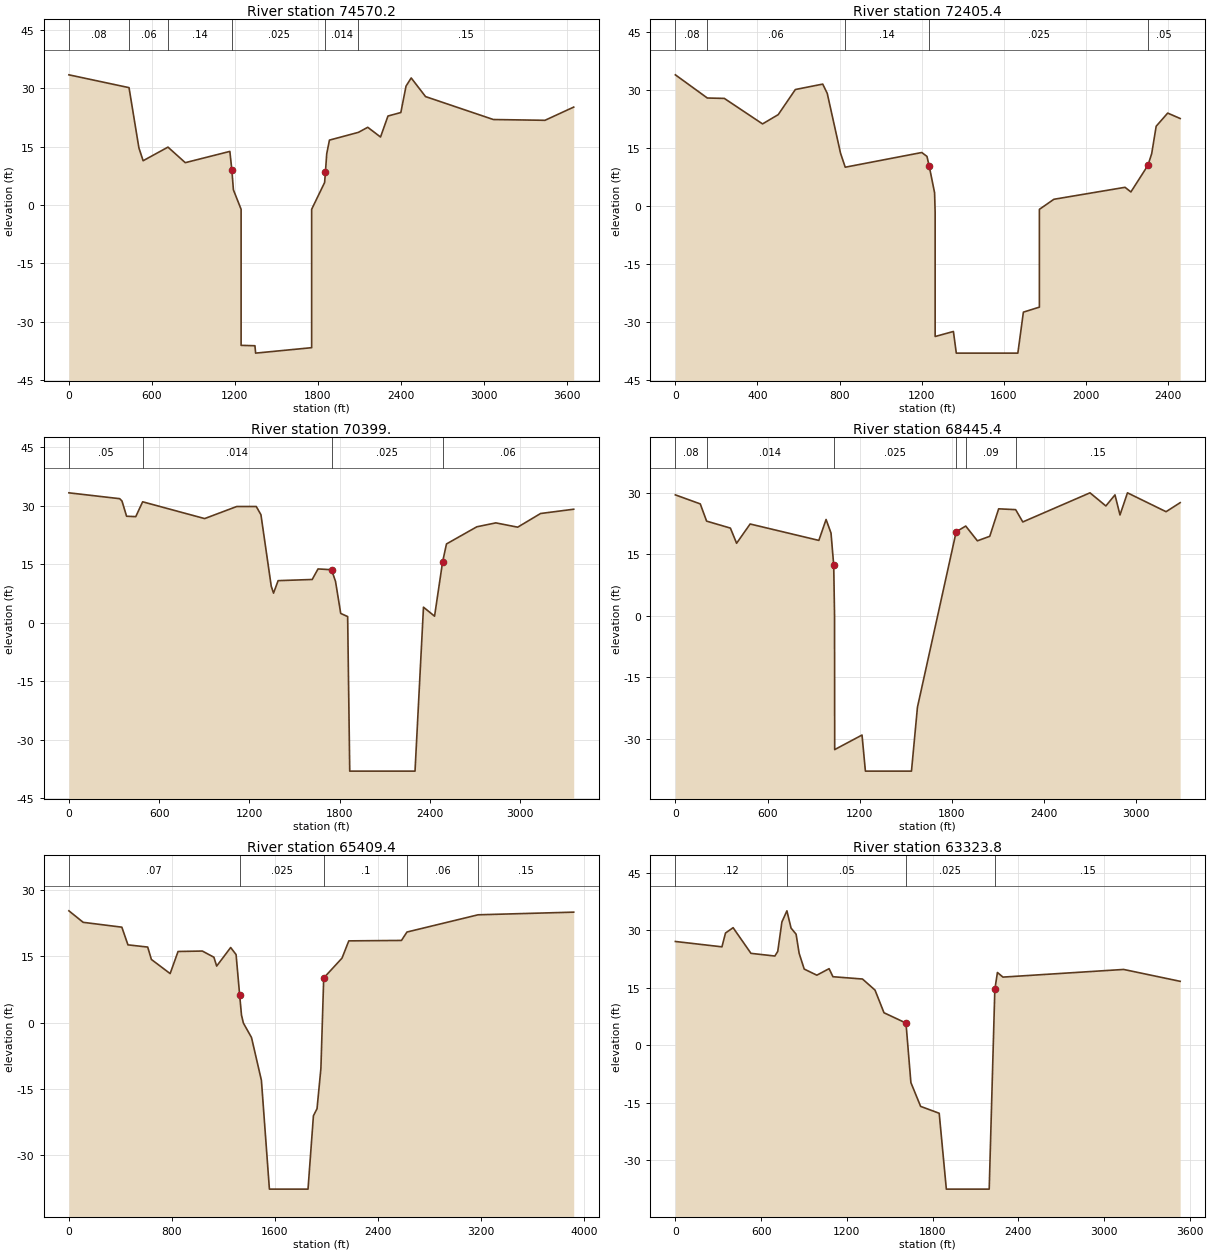
Type RM Length L Ch R = 1 ,74570.2 ,2100,2164.8,2160
#Sta/Elev= 30
       0    33.5  434.69    30.2  506.11    14.7  536.62    11.4  716.26    14.9
  841.35    10.9 1163.68    13.8 1177.76   9.138 1189.41     3.9    1245    -1.1
    1245   -36.1    1345   -36.2    1350   -38.1    1755   -36.7    1755    -1.1
 1848.85     5.8 1854.41     8.4 1864.11    13.2 1883.58    16.7 2093.07    18.7
 2160.66      20 2252.99    17.5 2306.76    22.9 2399.81    23.8 2437.42    30.6
 2474.67    32.7 2578.44    27.9 3068.72      22 3442.24    21.8 3649.66    25.2
#Mann= 6 ,-1 , 0
       0     .08       0  434.69     .06       0  716.26     .14       0
 1177.76    .025       0 1854.41    .014       0 2093.07     .15       0
#Block Obstruct= 2 , 0
          715.42   14.93
Bank Sta=1177.76,1854.41
XS Rating Curve= 0
Exp/Cntr=.3,.1

Type RM Length L Ch R = 1 ,72405.4 ,1520,2006.4,2480
#Sta/Elev= 30
       0    33.9  155.78    27.9  238.63    27.8  424.76    21.2  501.22    23.6
  584.75    30.1  718.08    31.5  740.18    29.1  804.96    13.6  827.79      10
 1200.78    13.8 1226.03    12.8 1237.37    10.2 1263.22     3.4    1266    -1.7
    1266   -33.8    1355   -32.5    1369   -38.1    1669   -38.1    1696   -27.5
    1774   -26.2    1774     -.9 1844.56     1.7 2191.34     4.8 2219.96     3.6
 2303.05    10.5 2321.21    13.5 2343.11    20.6 2399.29      24 2460.05    22.6
#Mann= 5 ,-1 , 0
       0     .08       0  155.78     .06       0  827.79     .14       0
 1237.37    .025       0 2303.05     .05       0
#Block Obstruct= 2 , 0
         1198.24   13.95
Bank Sta=1237.37,2303.05
XS Rating Curve= 0
Exp/Cntr=.3,.1

Type RM Length L Ch R = 1 ,70399.  ,1600,1953.6,2920
#Sta/Elev= 30
       0    33.3  337.59    31.8  352.84    31.2  383.35    27.3  444.37    27.2
  490.14      31  902.15    26.7 1115.74    29.8 1245.09    29.8  1276.3    27.7
 1344.71     9.4 1359.97     7.6  1390.5    10.8 1617.12    11.1 1655.68    13.8
 1745.65    13.6 1772.02    10.6 1806.55     2.4  1852.6     1.6  1866.5     -38
  2300.4     -38 2356.62       4 2430.22     1.7 2483.65    15.6 2509.35    20.2
 2711.27    24.6 2837.47    25.6 2982.67    24.5 3134.72      28 3355.02    29.1
#Mann= 4 ,-1 , 0
       0     .05       0  490.14    .014       0 1745.65    .025       0
 2483.65     .06       0
#Block Obstruct= 2 , 0
         1677.53   13.95
Bank Sta=1745.65,2483.65
XS Rating Curve= 0
Exp/Cntr=.3,.1

Type RM Length L Ch R = 1 ,68445.4 ,2560,3036,3080
#Sta/Elev= 30
       0    29.5  162.11    27.3  203.42    23.1  358.41    21.4   398.7    17.7
  486.76    22.4   934.4    18.4  981.43    23.5 1013.54    20.2  1031.1    12.4
  1036.5      .3  1037.5   -32.6  1215.5  -29.05  1237.5  -37.85  1537.5  -37.85
  1576.5  -22.25 1828.67    20.5 1890.85    21.9 1966.71    18.3 2047.39    19.4
 2105.32    26.1 2215.91    25.9 2262.51    22.9 2700.14      30 2803.46    26.8
 2862.87    29.5  2895.4    24.6  2944.2      30 3195.47    25.4 3287.35    27.6
#Mann= 6 ,-1 , 0
       0     .08       0  203.42    .014       0  1031.1    .025       0
 1828.67     .05       0 1890.85     .09       0 2215.91     .15       0
Bank Sta=1031.1,1828.67
XS Rating Curve= 0
Exp/Cntr=.3,.1

Type RM Length L Ch R = 1 ,65409.4 ,2560,2085.6,1720
#Sta/Elev= 30
       0    25.3   110.7    22.7  411.27    21.6  458.64    17.6  612.12    17.1
  640.67    14.3  786.38    11.1  847.86    16.1 1036.63    16.2 1126.46    14.8
 1147.89    12.8 1256.72      17 1298.72    15.4 1326.56     6.2 1340.73     1.7
  1355.5     -.1  1418.5   -3.37  1495.5  -13.07  1557.5  -37.67  1857.5  -37.67
  1899.5  -21.07  1927.5  -19.47  1957.5   -10.4 1979.41    10.1 2121.57    14.6
  2174.3    18.5 2583.46    18.6 2625.97    20.5 3178.53    24.4 3921.43      25
#Mann= 5 ,-1 , 0
       0     .07       0 1326.56    .025       0 1979.41      .1       0
 2625.97     .06       0 3178.53     .15       0
#Block Obstruct= 2 , 0
          835.71    14.8
Bank Sta=1326.56,1979.41
XS Rating Curve= 0
Exp/Cntr=.3,.1

Type RM Length L Ch R = 1 ,63323.8 ,2860,3115.2,2680
#Sta/Elev= 30
       0    27.1  325.93    25.7  350.83    29.3  404.06    30.7  529.17      24
  696.36    23.3  716.43    24.5  745.65    32.2  780.68    35.1   809.6    30.6
  844.93      29  866.35      24  901.68    19.9  990.06    18.3 1075.84      20
 1102.87    17.9 1309.68    17.3 1397.55    14.4 1460.09     8.5 1613.98     5.8
  1648.5   -9.74  1716.5  -15.94  1846.5  -17.74  1896.5  -37.54  2196.5  -37.54
 2235.94    14.6  2254.1      19 2292.77    17.8 3137.23    19.8 3533.09    16.7
#Mann= 4 ,-1 , 0
       0     .12       0  780.68     .05       0 1613.98    .025       0
 2235.94     .15       0
Bank Sta=1613.98,2235.94
XS Rating Curve= 0
Exp/Cntr=.3,.1

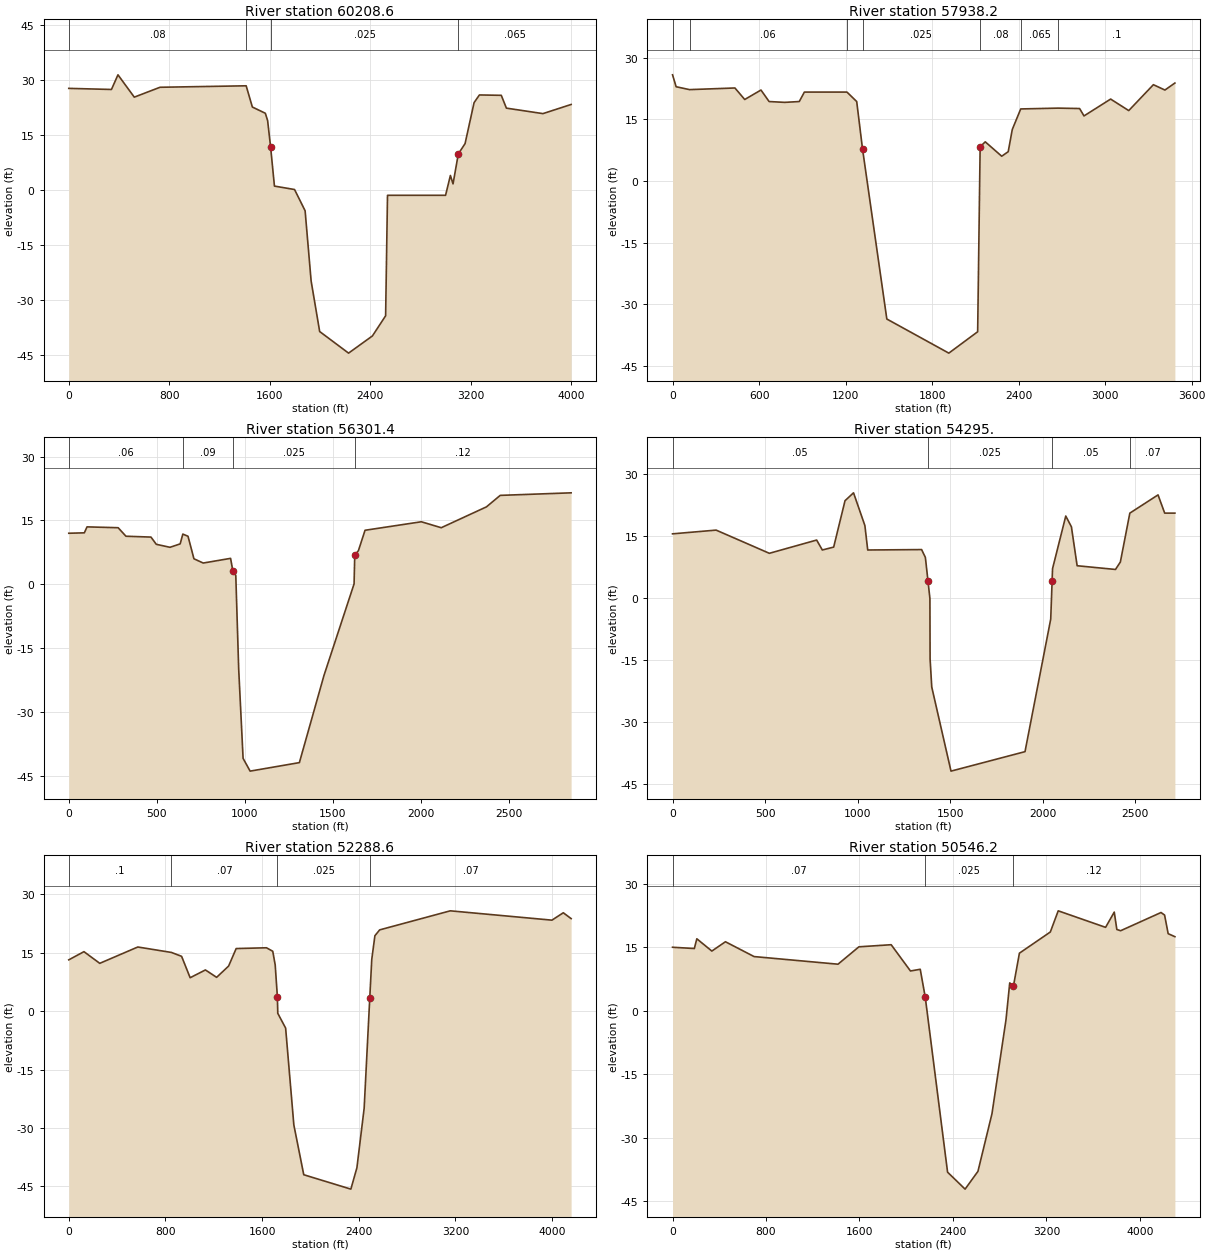
Type RM Length L Ch R = 1 ,60208.6 ,1940,2270.4,2800
#Sta/Elev= 30
       0    27.8  339.84    27.5  391.58    31.5   521.5    25.4  726.34    28.1
 1412.24    28.5 1461.53    22.7 1564.79      21 1583.07      19 1606.74    11.8
  1637.3     1.1  1797.5     .16  1881.5   -5.64  1929.5  -24.84  1997.5  -38.64
  2227.5  -44.54  2417.5  -39.84  2522.5  -34.34  2537.5   -1.42 2999.77   -1.42
 3038.27       4 3059.23     1.7  3101.3     9.9 3154.95    12.7 3226.75    23.9
 3269.27      26 3443.36    25.9 3483.98    22.4 3774.89    20.9 3999.38    23.4
#Mann= 4 ,-1 , 0
       0     .08       0 1412.24     .05       0 1606.74    .025       0
  3101.3    .065       0
Bank Sta=1606.74,3101.3
XS Rating Curve= 0
Exp/Cntr=.3,.1

Type RM Length L Ch R = 1 ,57938.2 ,1200,1636.8,1800
#Sta/Elev= 30
       0    25.8   24.91    22.9  117.95    22.2  432.65    22.6  500.55    19.8
  613.27    22.1  669.63    19.3   777.6    19.1  878.83    19.3  914.27    21.6
 1209.67    21.6 1277.16    19.3 1317.76     7.7    1486   -33.6    1916   -41.9
    2116   -36.7 2133.21     8.3 2168.68     9.5  2282.8       6 2327.87     7.1
 2356.07    12.5 2414.63    17.5  2674.3    17.7 2823.03    17.6 2853.42    15.8
  3038.1    19.9 3163.82    17.1  3334.7    23.4 3414.79    22.1 3483.75    23.8
#Mann= 7 ,-1 , 0
       0     .12       0  117.95     .06       0 1209.67     .05       0
 1317.76    .025       0 2133.21     .08       0 2414.63    .065       0
  2674.3      .1       0
#Block Obstruct= 2 , 0
                         2177.09            9.07
Bank Sta=1317.76,2133.21
XS Rating Curve= 0
Exp/Cntr=.3,.1

Type RM Length L Ch R = 1 ,56301.4 ,1800,2006.4,1950
#Sta/Elev= 30
       0      12   88.49    12.1  103.76    13.5  280.71    13.3  325.02    11.3
  467.37    11.1  497.54     9.4   575.5     8.7   633.3     9.5  648.38    11.8
  677.83    11.3  711.59       6  764.33       5   919.9     6.1   932.6     3.2
  949.48     2.1     966   -19.9     991   -40.9    1031   -43.9    1311   -41.9
    1451   -21.4    1622      .1 1625.88     6.9 1646.59     7.9 1684.33    12.7
 2004.41    14.7 2117.47    13.3 2374.63    18.2  2452.9    20.9 2855.99    21.5
#Mann= 4 ,-1 , 0
       0     .06       0  648.38     .09       0   932.6    .025       0
 1625.88     .12       0
#Block Obstruct= 2 , 0
          660.79   12.23
Bank Sta=932.6,1625.88
XS Rating Curve= 0
Exp/Cntr=.3,.1

Type RM Length L Ch R = 1 ,54295.  ,2500,2006.4,1720
#Sta/Elev= 30
       0    15.5  235.52    16.4  523.31    10.8  778.86      14  809.54    11.6
  870.89    12.3  932.23    23.5  978.24    25.4 1039.59    17.5 1054.93    11.6
 1346.18    11.7 1366.59     9.8 1380.79    4.04    1391    -.08    1392  -14.68
    1401  -21.48    1505  -41.78    1905  -37.08    2044   -5.08 2051.49    4.14
 2053.91     7.1 2125.32    19.8  2155.8    17.2 2186.75     7.8 2394.06     6.9
 2420.39     8.7 2471.61    20.5 2624.07    24.9 2659.98    20.5 2715.08    20.5
#Mann= 4 ,-1 , 0
       0     .05       0 1380.79    .025       0 2051.49     .05       0
 2471.61     .07       0
#Block Obstruct= 2 , 0
         1130.36    13.2 2161.61            13.2
Bank Sta=1380.79,2051.49
XS Rating Curve= 0
Exp/Cntr=.3,.1

Type RM Length L Ch R = 1 ,52288.6 ,1680,1742.4,1840
#Sta/Elev= 30
       0    13.2  125.66    15.3  256.47    12.3  571.36    16.5  849.56    15.1
  933.88    14.1  1004.6     8.6 1130.97    10.6 1223.81     8.7 1323.03    11.6
 1385.58    16.1 1636.42    16.3 1688.46    15.4 1708.62    11.9 1726.68     3.7
    1730    -.55    1795   -4.35    1863  -29.25    1945  -42.05    2335  -45.75
    2385  -40.25    2445  -24.95 2491.52    3.45 2507.91    13.3 2533.98    19.4
 2573.31    20.9 3158.03    25.8 3999.36    23.4 4093.38    25.3  4158.2    23.8
#Mann= 4 ,-1 , 0
       0      .1       0  849.56     .07       0 1726.68    .025       0
 2491.52     .07       0
#Block Obstruct= 2 , 0
            1375   14.34
Bank Sta=1726.68,2491.52
XS Rating Curve= 0
Exp/Cntr=.3,.1

Type RM Length L Ch R = 1 ,50546.2 ,1640,2059.2,2350
#Sta/Elev= 30
       0      15  186.45    14.7  207.88      17  336.41    14.1  452.64    16.3
  698.02    12.8 1416.15      11 1594.91    15.1 1871.21    15.6  2036.4     9.4
 2119.98     9.8 2163.05     3.2    2354   -38.1    2504   -42.1    2614   -37.9
    2734   -24.3    2854   -2.12    2886    6.58  2918.2     5.9 2968.81    13.6
 3233.45    18.6 3301.01    23.6 3706.33    19.7  3780.6    23.3 3802.68    19.2
 3834.97    18.9 4180.79    23.2 4211.38    22.6  4242.1    18.2 4299.53    17.5
#Mann= 3 ,-1 , 0
       0     .07       0 2163.05    .025       0  2918.2     .12       0
#Block Obstruct= 2 , 0
         1495.54   13.49
Bank Sta=2163.05,2918.2
XS Rating Curve= 0
Exp/Cntr=.3,.1

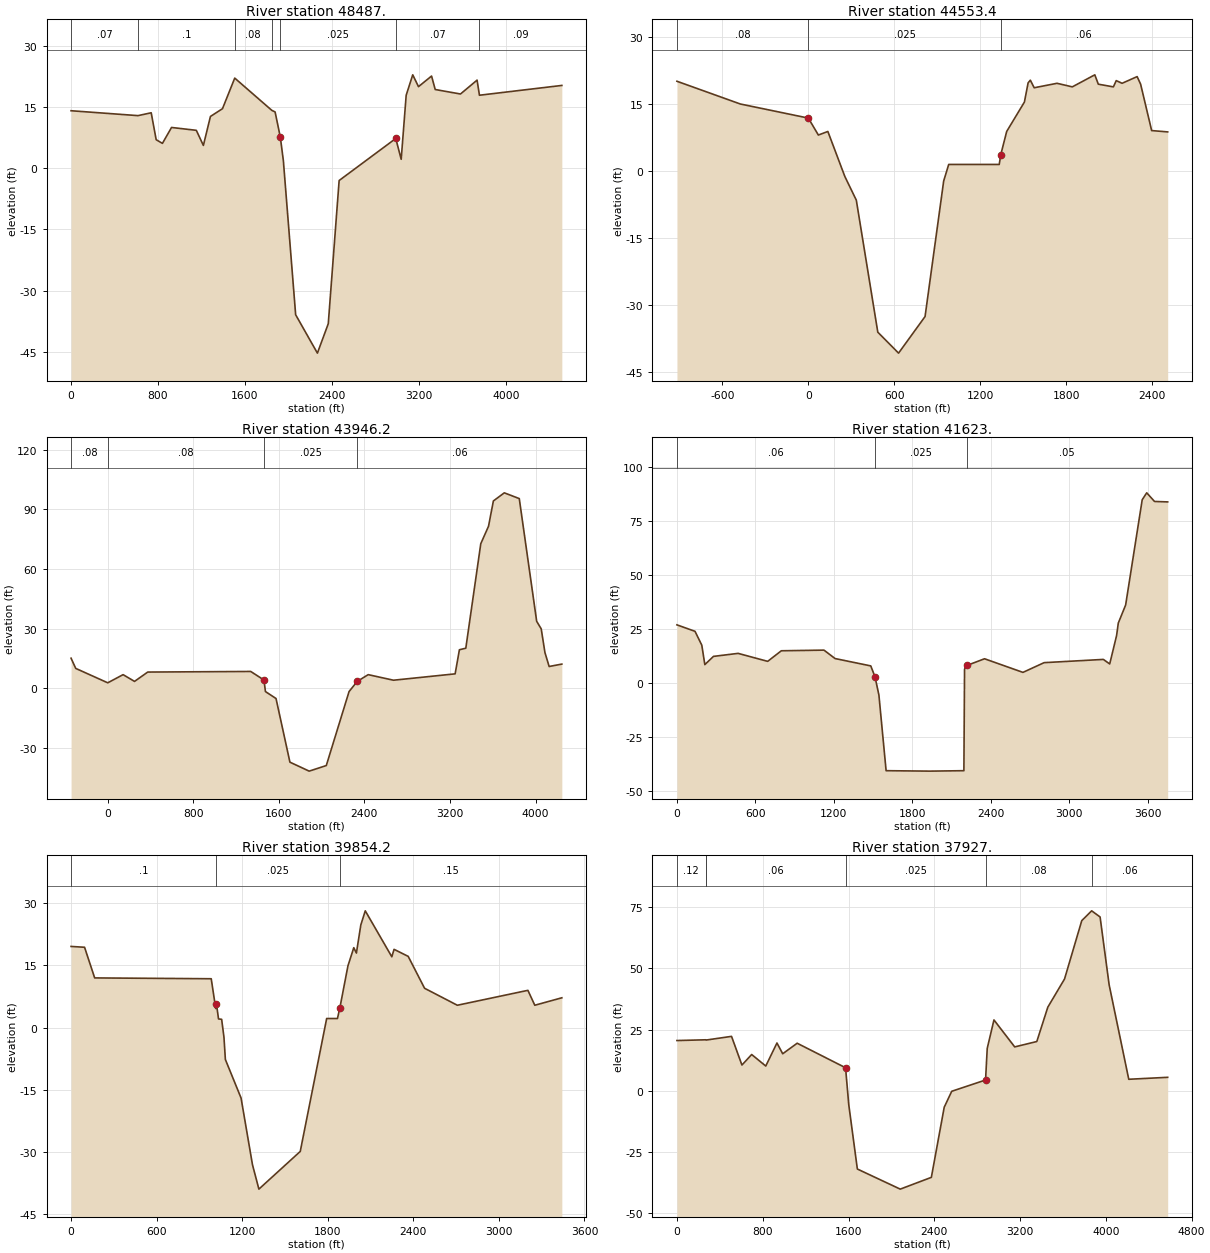
Type RM Length L Ch R = 1 ,48487.  ,3400,3933.6,4500
#Sta/Elev= 30
       0    14.1  615.76    12.9  737.03    13.6  782.91       7  840.26     6.1
  924.22      10 1152.07     9.3 1217.07     5.6 1282.08    12.7 1392.88    14.6
 1505.56    22.1 1846.44    14.2 1877.01    13.8 1925.05    7.61  1952.8     1.9
    2066   -35.9    2266   -45.3    2366   -38.1    2466      -3 2986.92     7.3
 3036.86     2.2 3082.76    17.9 3143.02    22.9 3196.01      20 3316.22    22.6
 3349.79    19.3 3582.39    18.2 3734.86    21.6  3756.8    17.9 4514.67    20.3
#Mann= 7 ,-1 , 0
       0     .07       0  615.76      .1       0 1505.56     .08       0
 1846.44      .1       0 1925.05    .025       0 2986.92     .07       0
  3756.8     .09       0
#Block Obstruct= 2 , 0
         1321.43   12.92 2987.69            7.23
Bank Sta=1925.05,2986.92
XS Rating Curve= 0
Exp/Cntr=.3,.1

Type RM Length L Ch R = 1 ,44553.4 ,520,607.2,520
#Sta/Elev= 30
 -917.3720.15846 -474.7715.05884       0    11.9   70.06     8.1  136.36     8.9
     255    -1.2     335    -6.5     485   -36.1     630   -40.8     815   -32.6
     945    -2.2     980     1.5 1332.84     1.5 1343.61     3.7 1384.88     8.9
  1508.7    15.5 1534.44    19.8 1549.98    20.4 1576.88    18.7  1736.4    19.7
 1842.93    18.9  2000.1    21.6 2024.54    19.5 2129.88    18.9 2149.67    20.3
 2190.58    19.7  2295.7    21.2 2320.04    19.5 2397.01     9.1 2508.98     8.8
#Mann= 3 ,-1 , 0
 -917.37     .08       0       0    .025       0 1343.61     .06       0
#Block Obstruct= 2 , 0
                         2333.04           14.34
Bank Sta=0,1343.61
XS Rating Curve= 0
Exp/Cntr=.3,.1

Type RM Length L Ch R = 1 ,43946.2 ,2600,2323.2,2140
#Sta/Elev= 30
 -342.9415.15617 -299.3210.03261       0     2.8  143.66     6.9  250.34     3.5
  373.96     8.2 1336.96     8.5 1460.72     4.2  1474.5    -1.6  1573.5    -5.1
  1703.5   -37.1  1883.5   -41.6  2043.5   -38.8  2256.5    -1.6 2332.79     3.5
 2435.52     6.9 2671.75     4.1 3248.35     7.3 3288.28    19.4 3348.18    20.2
 3488.07    72.7 3560.56    81.5 3605.91    94.2 3708.08    98.3 3848.09    95.4
  4010.9    33.7 4053.41    29.9 4088.11      18 4127.45      11 4246.12    12.2
#Mann= 4 ,-1 , 0
 -342.94     .08       0       0     .08       0 1460.72    .025       0
 2332.79     .06       0
#Block Obstruct= 2 , 0
          924.11    8.33 2589.29            6.62
Bank Sta=1460.72,2332.79
XS Rating Curve= 0
Exp/Cntr=.3,.1

Type RM Length L Ch R = 1 ,41623.  ,2040,1768.8,1650
#Sta/Elev= 30
       0    27.1  138.26    24.1  190.15    17.7   213.4     8.7  279.55    12.5
  467.95    13.9  694.15    10.2   798.6    15.1  1124.7    15.4 1209.61    11.5
 1482.71     8.1 1515.26       3    1545    -5.4    1600   -40.4    1935   -40.6
    2195   -40.4 2200.03     6.6 2217.53     8.3 2353.02    11.4 2646.76     5.1
 2808.62     9.6 3261.82    11.1 3310.38       9 3363.22    22.2 3376.04    27.9
 3432.32    36.3    3559      85 3593.55    88.2 3653.24    84.2 3753.94      84
#Mann= 3 ,-1 , 0
       0     .06       0 1515.26    .025       0 2217.53     .05       0
#Block Obstruct= 2 , 0
          292.86   13.45 2352.83           11.37
Bank Sta=1515.26,2217.53
XS Rating Curve= 0
Exp/Cntr=.3,.1

Type RM Length L Ch R = 1 ,39854.2 ,2050,1927.2,1760
#Sta/Elev= 30
       0    19.6   94.58    19.4  165.48      12  982.79    11.8  1014.3     4.6
 1019.47     5.7 1033.93     2.1 1055.86       2    1072    -2.3    1082    -7.7
    1192     -17    1272   -33.1    1317     -39    1607   -29.9 1792.31     2.2
 1867.95     2.2 1885.01     4.8 1941.37    14.9 1982.43    19.3 2000.74      18
 2031.81    24.8 2062.89    28.2 2249.14    17.1 2264.91    18.9 2363.99    17.2
 2478.84     9.5 2708.54     5.4 3203.36       9 3251.74     5.4 3441.34     7.2
#Mann= 3 ,-1 , 0
       0      .1       0 1019.47    .025       0 1885.01     .15       0
#Block Obstruct= 2 , 0
                            2400           13.56
Bank Sta=1019.47,1885.01
XS Rating Curve= 0
Exp/Cntr=.3,.1

Type RM Length L Ch R = 1 ,37927.  ,1360,1108.8,800
#Sta/Elev= 30
       0    20.5  268.74    20.8  272.51    20.7  509.04    22.2   606.2    10.5
  696.96    14.8   828.4    10.1  932.73    19.5   986.3    15.1 1121.26    19.4
 1572.47     9.4  1602.5    -5.7  1682.5   -31.9  2082.5   -40.1  2372.5   -35.3
  2492.5    -6.7  2562.5     -.2 2877.97     4.4 2893.64    17.3 2956.33    28.9
  3149.8    17.9 3355.97    20.1 3458.54    34.1  3614.5    45.6 3775.21    69.4
 3867.43    73.4 3946.06    70.9 4030.58    43.2 4213.41     4.7 4576.49     5.5
#Mann= 6 ,-1 , 0
       0     .12       0  268.74     .08       0  272.51     .06       0
 1572.47    .025       0 2877.97     .08       0 3867.43     .06       0
#Block Obstruct= 2 , 0
                         4093.75           19.22
Bank Sta=1572.47,2877.97
XS Rating Curve= 0
Exp/Cntr=.3,.1

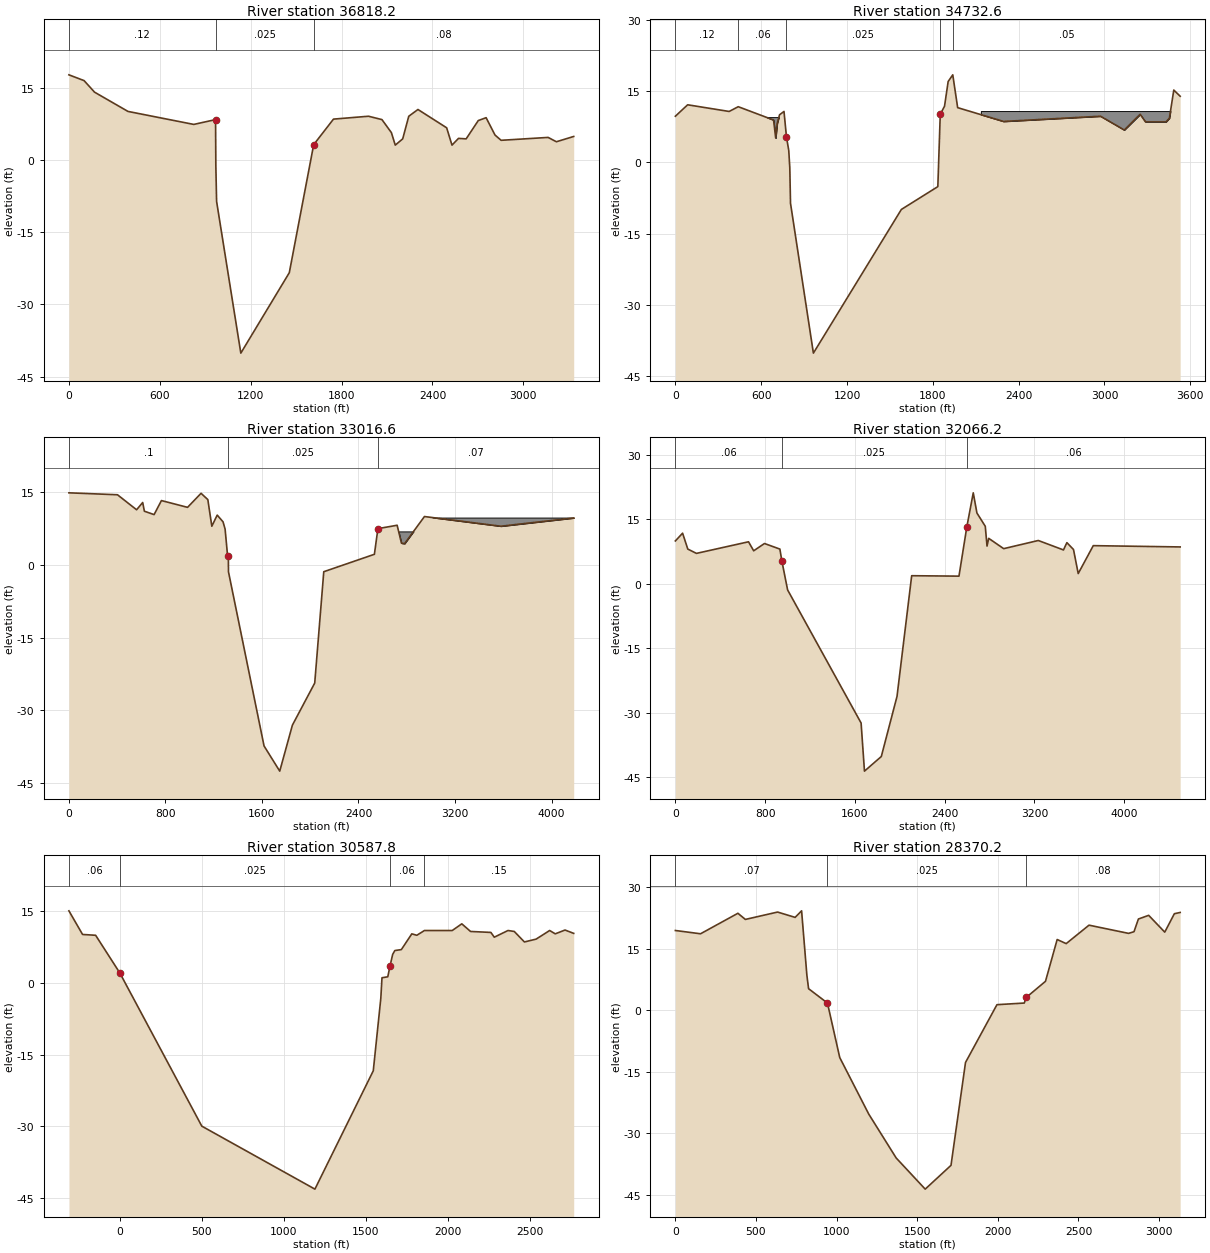
Type RM Length L Ch R = 1 ,36818.2 ,2080,2085.6,2440
#Sta/Elev= 30
       0    17.7  100.11    16.5  169.31    14.1  389.83    10.1  824.34     7.4
  968.14     8.4     970    -1.1     975    -8.6    1135   -40.1    1455   -23.4
 1615.99     3.2 1746.65     8.5 1977.75     9.1 2066.63     8.4 2128.96     5.7
 2154.48     3.1  2203.6     4.4 2243.69     9.1 2304.38    10.5 2493.74     6.7
 2529.02     3.1 2572.03     4.5 2622.49     4.4 2702.46     8.2 2754.23     8.8
 2812.91     5.2 2853.15     4.1 3163.47     4.7 3218.41     3.8 3332.53     4.9
#Mann= 3 , 0 , 0
       0     .12       0  968.14    .025       0 1615.99     .08       0
#Block Obstruct= 2 , 0
                         2006.25            9.04
Bank Sta=968.14,1615.99
XS Rating Curve= 0
Exp/Cntr=.3,.1

Type RM Length L Ch R = 1 ,34732.6 ,1720,1716,1560
#Sta/Elev= 30
       0     9.7   85.82    12.1  376.04    10.7  439.56    11.7  686.64     8.9
  701.53     5.1  712.21     8.2  728.34      10  759.47    10.7  776.91     5.3
  792.75     2.5     800    -1.1     805    -8.6     965   -40.1    1580    -9.9
    1835    -5.1 1851.98    10.1 1881.79    11.8 1907.27      17 1939.45    18.4
 1973.66    11.5 2294.75     8.6  2972.5     9.7 3138.63     6.8 3249.66    10.1
 3287.02     8.5 3430.19     8.5 3454.06     9.3 3484.78    15.2 3529.34    13.9
#Mann= 5 ,-1 , 0
       0     .12       0  439.56     .06       0  776.91    .025       0
 1851.98     .08       0 1939.45     .05       0
#Block Obstruct= 2 ,-1
  641.41  743.61    9.51 2135.71 3529.34   10.78
Bank Sta=776.91,1851.98
XS Rating Curve= 0
Exp/Cntr=.3,.1

Type RM Length L Ch R = 1 ,33016.6 ,920,950.4,1000
#Sta/Elev= 30
       0    14.9  402.63    14.5  561.04    11.4  611.53    12.9  625.64    11.1
  706.11    10.4  766.85    13.3  983.57    11.9 1095.24    14.8  1151.5    13.5
 1184.59       8 1229.26    10.3 1277.63     8.9 1294.73     7.4 1315.49     1.8
 1321.72     1.7  1322.5    -1.4  1617.5   -37.4  1747.5   -42.6  1852.5   -33.1
  2037.5   -24.4  2112.5    -1.4 2532.08     2.2 2561.27     7.5 2720.62     8.2
 2756.32     4.5  2782.3     4.4 2947.07      10 3580.72       8 4184.08     9.7
#Mann= 3 , 0 , 0
       0      .1       0 1315.49    .025       0 2561.27     .07       0
#Block Obstruct= 2 ,-1
 2704.85 2881.06    6.93 2950.89 4184.08    9.79
Bank Sta=1315.49,2561.27
XS Rating Curve= 0
Exp/Cntr=.3,.1

Type RM Length L Ch R = 1 ,32066.2 ,2280,1478.4,700
#Sta/Elev= 30
       0      10   64.32    11.8  110.76     8.1  187.98     7.1   651.8     9.8
   697.8     7.7  793.96     9.4  931.21     8.1  949.24     5.3    1000    -1.4
    1655   -32.4    1685   -43.6    1835   -40.2    1975   -26.2 2105.74     1.9
 2527.08     1.8 2596.65    13.2 2654.36    21.2  2687.1    16.5 2761.58    13.4
 2776.98     8.8 2792.04    10.6 2925.48     8.2 3233.98    10.1 3458.31     7.9
 3488.67     9.6 3547.63       8 3589.61     2.4  3723.8     8.9 4498.13     8.6
#Mann= 3 ,-1 , 0
       0     .06       0  949.24    .025       0 2596.65     .06       0
#Block Obstruct= 2 , 0
          790.18    9.22 2741.07           12.35
Bank Sta=949.24,2596.65
XS Rating Curve= 0
Exp/Cntr=.3,.1

Type RM Length L Ch R = 1 ,30587.8 ,2050,2217.6,2300
#Sta/Elev= 30
 -310.6915.12513 -227.3710.17252  -147.69.998375       0     2.1     500     -30
    1190   -43.2    1546   -18.4    1592    -3.2 1599.07     1.1  1634.5     1.3
 1647.66     3.5 1664.37       6 1677.55     6.8 1717.31       7 1780.98    10.3
 1811.65      10  1858.2      11 2027.79      11 2085.98    12.4 2139.39    10.8
 2263.21    10.6 2284.13     9.6 2367.86      11 2405.98    10.8 2467.96     8.6
 2539.57     9.2 2621.91      11 2656.06    10.3  2715.6    11.1 2768.61    10.4
#Mann= 4 ,-1 , 0
 -310.69     .06       0       0    .025       0 1647.66     .06       0
  1858.2     .15       0
Bank Sta=0,1647.66
XS Rating Curve= 0
Exp/Cntr=.3,.1

Type RM Length L Ch R = 1 ,28370.2 ,1560,1557.6,1440
#Sta/Elev= 30
       0    19.5  156.18    18.7  387.84    23.7  434.08    22.2  633.87      24
   742.7    22.7  782.88    24.3  815.61     8.6  826.24     5.3  943.28     1.8
  1019.5   -11.5  1199.5   -25.3  1369.5     -36  1549.5   -43.6  1709.5   -37.8
  1799.5   -12.7 1994.48     1.4 2163.77     1.8 2177.22     3.2 2295.52     7.1
 2368.02    17.3 2423.92    16.3 2565.49    20.8 2810.75    18.8 2844.46    19.2
 2871.77    22.3  2935.5    23.2  3035.3    19.1 3094.82    23.6 3130.88    23.9
#Mann= 3 , 0 , 0
       0     .07       0  943.28    .025       0 2177.22     .08       0
Bank Sta=943.28,2177.22
XS Rating Curve= 0
Exp/Cntr=.3,.1