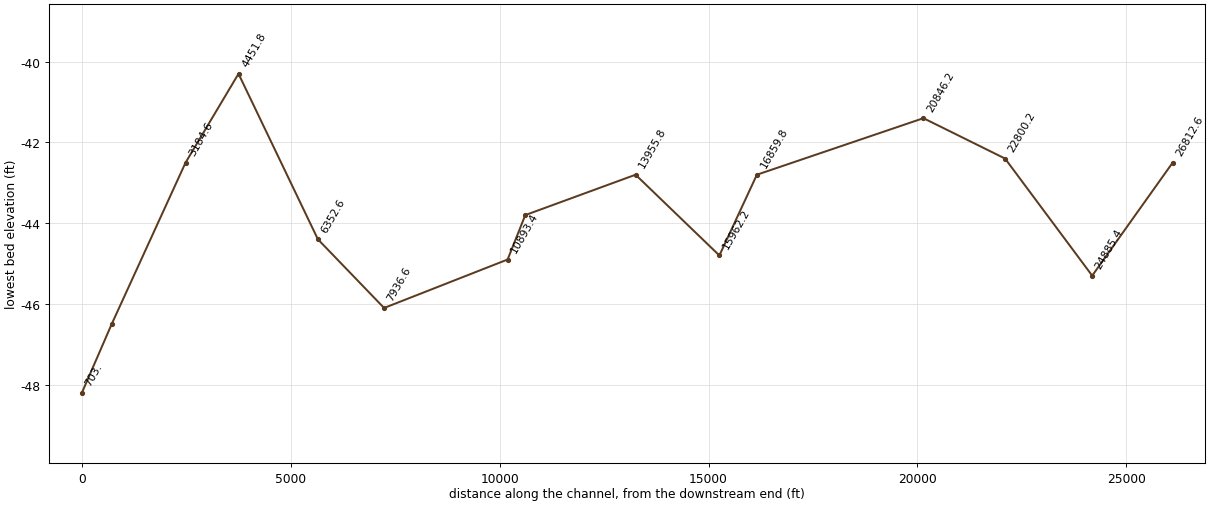
HEC-RAS study G100-00-00.prj: G100-00-00

--- G100-00-00.g01 (geometry) --- (continued)

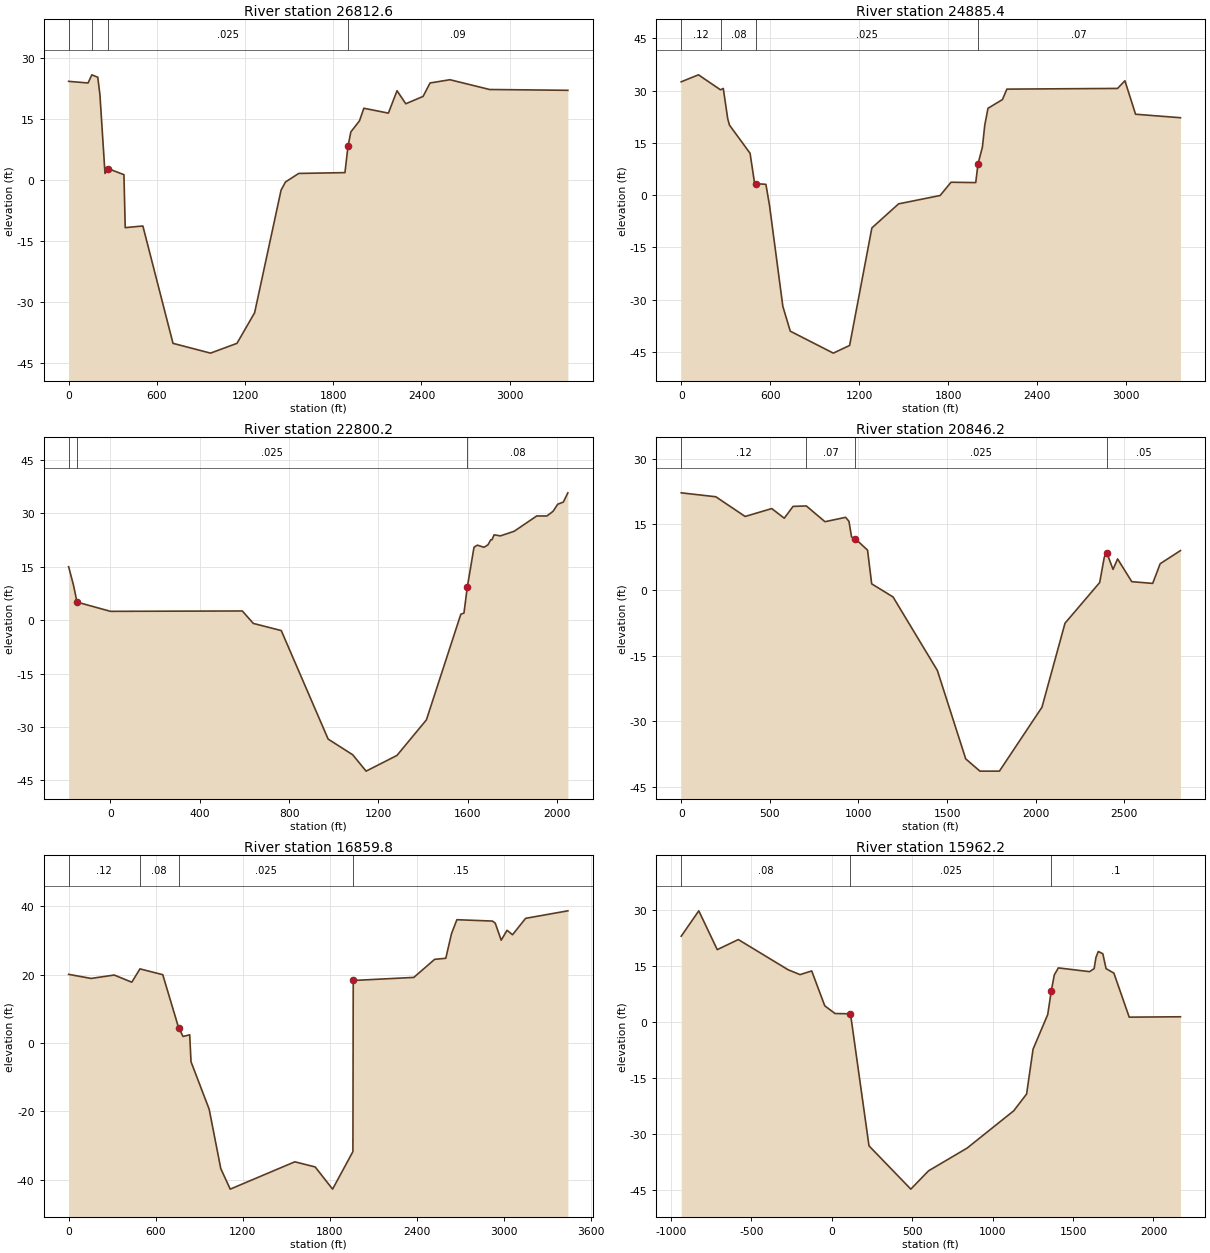
Type RM Length L Ch R = 1 ,26812.6 ,1580,1927.2,2480
#Sta/Elev= 30
       0    24.2  132.22    23.8  158.15    25.8  198.42    25.2  213.17    20.8
  247.42     1.6  267.24     2.8   376.2     1.3     385   -11.7     505   -11.3
     710   -40.1     965   -42.5    1145   -40.1    1265   -32.6    1445    -2.5
    1475     -.5 1565.01     1.6 1879.48     1.8 1900.39     8.3 1919.81    11.8
 1978.16    14.5 2008.18    17.6 2174.96    16.4 2233.79    21.9 2293.33    18.7
 2410.84    20.5 2458.42    23.8 2593.49    24.6 2863.63    22.2 3395.69      22
#Mann= 4 ,-1 , 0
       0     .12       0  158.15     .05       0  267.24    .025       0
 1900.39     .09       0
Bank Sta=267.24,1900.39
XS Rating Curve= 0
Exp/Cntr=.3,.1

Type RM Length L Ch R = 1 ,24885.4 ,2000,2085.2,2160
#Sta/Elev= 30
       0    32.5  116.25    34.5     265    30.2   283.5    30.6   313.5    21.9
     325    20.1  464.12      12     495     3.3  504.98     3.3  570.78     3.1
     595    -2.9     685   -31.9     735     -39    1025   -45.3    1135   -43.1
    1285    -9.4    1465    -2.5    1745     -.1  1818.6     3.7  1985.1     3.6
 2000.11     8.9 2030.12    13.8 2045.75      20 2067.62    24.9 2164.95    27.4
  2194.9    30.4 2940.88    30.6 2990.48    32.8 3062.35    23.2 3364.86    22.2
#Mann= 4 ,-1 , 0
       0     .12       0     265     .08       0  504.98    .025       0
 2000.11     .07       0
Bank Sta=504.98,2000.11
XS Rating Curve= 0
Exp/Cntr=.3,.1

Type RM Length L Ch R = 1 ,22800.2 ,2000,1954,1950
#Sta/Elev= 30
 -187.2415.03532 -165.879.963838 -149.555.097109       0     2.5  590.57     2.6
     640     -.9     765    -2.9     975   -33.4    1085   -37.8    1145   -42.4
    1283     -38    1415     -28 1569.26     1.7 1583.16       2 1598.16     9.3
 1628.16    20.5 1643.16    21.1 1673.16    20.5 1690.91    21.2 1703.16    22.6
 1708.66    22.6 1718.16      24 1746.66    23.7 1808.16      25 1909.14    29.3
 1954.75    29.3 1982.04    30.6 2003.21    32.6 2028.27    33.2 2048.51    35.8
#Mann= 3 , 0 , 0
 -187.24     .06       0 -149.55    .025       0 1598.16     .08       0
Bank Sta=-149.55,1598.16
XS Rating Curve= 0
Exp/Cntr=.3,.1

Type RM Length L Ch R = 1 ,20846.2 ,3600,3986.4,4100
#Sta/Elev= 30
       0    22.2   195.2    21.3   360.6    16.8  510.73    18.6  581.34    16.4
  630.83    19.1   705.9    19.2  810.99    15.6  927.35    16.6   946.1    15.7
  961.11    12.1  982.13    11.7 1051.19     9.1 1074.48     1.4    1195    -1.6
    1445   -18.4    1605   -38.6    1685   -41.4    1795   -41.4    2035   -26.8
    2165    -7.6 2360.62     1.7 2386.63     7.5 2401.63     8.4 2436.04     4.7
 2461.63     7.1 2541.64     1.9  2659.6     1.5 2701.96       6 2816.26       9
#Mann= 4 ,-1 , 0
       0     .12       0   705.9     .07       0  982.13    .025       0
 2401.63     .05       0
#Block Obstruct= 2 , 0
                         2410.53            7.82
Bank Sta=982.13,2401.63
XS Rating Curve= 0
Exp/Cntr=.3,.1

Type RM Length L Ch R = 1 ,16859.8 ,900,897.6,1600
#Sta/Elev= 30
       0    20.1  155.17    18.9  314.04    19.9  435.05    17.8  491.26    21.7
  648.36      20   757.3     4.5  788.11     1.9  833.81     2.4     843    -5.5
     968   -19.4    1048   -36.8    1113   -42.8    1558   -34.8    1698   -36.3
    1818   -42.8    1958   -31.8 1960.19    18.3 2377.27    19.2 2521.17    24.5
 2597.62    24.8 2636.95      32 2674.05    36.1 2919.31    35.7 2938.23    35.1
 2979.26    30.1 3019.55      33 3057.31    31.7 3147.37    36.5 3438.38    38.7
#Mann= 4 ,-1 , 0
       0     .12       0  491.26     .08       0   757.3    .025       0
 1960.19     .15       0
Bank Sta=757.3,1960.19
XS Rating Curve= 0
Exp/Cntr=.3,.1

Type RM Length L Ch R = 1 ,15962.2 ,1680,2006.4,2480
#Sta/Elev= 30
  -936.7      23 -827.41    29.8 -712.66    19.4 -581.66    22.1 -271.79      14
 -197.62    12.7  -125.3   13.69   -44.1    4.34   19.88    2.27  115.88     2.2
     231   -33.2     491   -44.8     601   -39.9     841   -33.8    1131   -23.8
    1211   -19.3    1251    -7.3 1342.29       2 1363.93     8.2 1382.99    12.6
 1408.28    14.5 1602.15    13.5 1630.82    14.3 1642.16    17.3 1656.61    18.9
 1684.89    18.3 1705.22    14.3 1753.79    13.1 1849.04     1.3 2167.63     1.4
#Mann= 3 ,-1 , 0
  -936.7     .08       0  115.88    .025       0 1363.93      .1       0
#Block Obstruct= 2 , 0
                         1731.25           10.07
Bank Sta=115.88,1363.93
XS Rating Curve= 0
Exp/Cntr=.3,.1

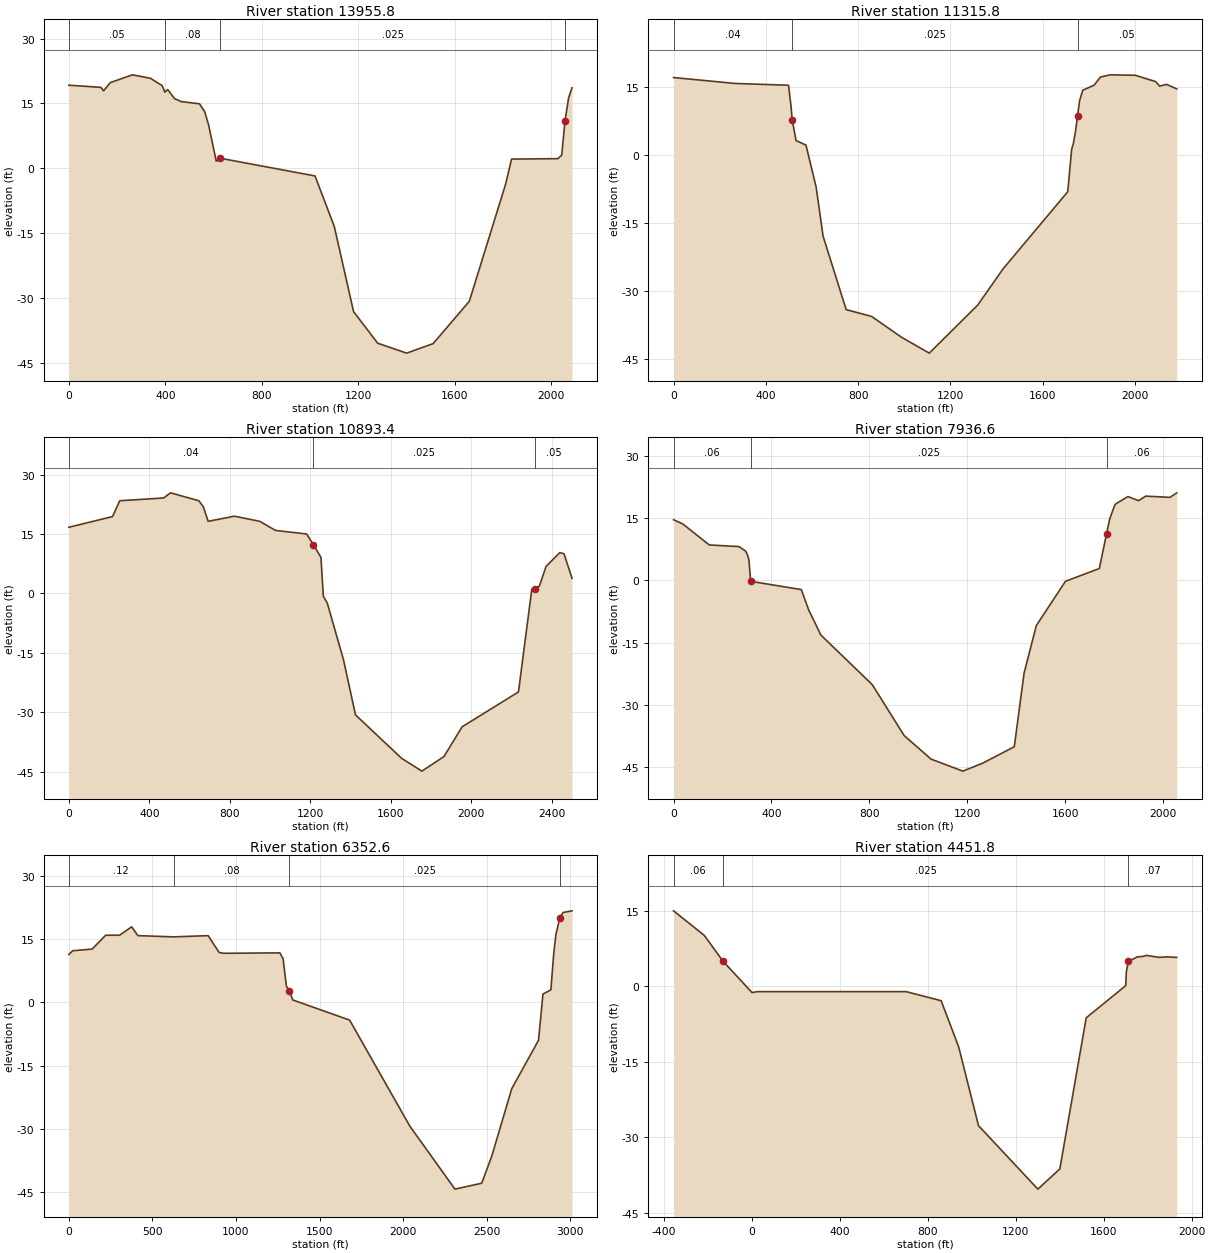
Type RM Length L Ch R = 1 ,13955.8 ,2600,2640,2640
#Sta/Elev= 30
       0    19.2     133    18.7  144.38    17.9     172    19.8  263.84    21.6
  338.57    20.8  387.17    19.1  398.47    17.6   410.1    18.2  438.28    16.1
  466.97    15.4  541.94    14.9  563.28    13.1  579.33    10.1  611.43     1.6
  627.48     2.3    1021    -1.8    1101   -13.5    1181   -33.2    1281   -40.5
    1401   -42.8    1511   -40.6    1661   -30.8    1811    -3.8 1836.21     2.1
 2028.14     2.2 2044.13       3  2057.7    10.9 2072.87    16.3 2086.99    18.6
#Mann= 4 ,-1 , 0
       0     .05       0  398.47     .08       0  627.48    .025       0
  2057.7     .06       0
Bank Sta=627.48,2057.7
XS Rating Curve= 0
Exp/Cntr=.3,.1

Type RM Length L Ch R = 1 ,11315.8 ,240,422.4,1000
#Sta/Elev= 30
       0      17   266.2    15.7  498.29    15.3  509.25    10.6  513.98     7.7
  530.89     3.1   573.8     2.1     618    -7.2     648     -18     748   -34.2
     858   -35.7     988   -40.3    1108   -43.8    1318   -33.2    1428   -25.2
    1708    -8.2  1725.1     1.2 1732.19     2.4 1741.64     5.1 1750.63    8.56
  1759.4    11.9 1773.09    14.2  1821.9    15.3  1849.7    17.1    1892    17.6
 2000.76    17.5  2089.3    16.1 2106.37    15.1 2135.66    15.5 2180.38    14.5
#Mann= 3 , 0 , 0
       0     .04       0  513.98    .025       0 1750.63     .05       0
Bank Sta=513.98,1750.63
XS Rating Curve= 0
Exp/Cntr=.3,.1

Type RM Length L Ch R = 1 ,10893.4 ,2800,2956.8,2940
#Sta/Elev= 30
       0    16.7  217.15    19.4  253.27    23.4  471.29    24.1  505.72    25.4
  646.31    23.4  668.32    21.9  692.52    18.2  823.22    19.5   948.8    18.2
 1027.54    15.9 1182.06      15 1215.66    12.3 1253.26     9.1    1265     -.7
    1285    -2.5    1365   -16.7    1425   -30.7    1655   -41.7    1755   -44.9
    1865   -41.2    1955   -33.7    2235   -24.9 2301.48     1.1  2316.1       1
 2339.46     1.9    2372     6.8 2440.57    10.3 2461.37      10 2501.28     3.8
#Mann= 3 ,-1 , 0
       0     .04       0 1215.66    .025       0  2316.1     .05       0
#Block Obstruct= 2 , 0
                         2461.61            9.22
Bank Sta=1215.66,2316.1
XS Rating Curve= 0
Exp/Cntr=.3,.1

Type RM Length L Ch R = 1 ,7936.6  ,1360,1584,1740
#Sta/Elev= 30
       0    14.7   37.16    13.7  145.94     8.6   267.2     8.2  294.54     7.1
  301.99     6.2   308.1     4.9  315.03     -.2  522.03    -2.2  552.03    -7.1
  602.03   -13.2  812.03   -25.2  942.03   -37.5 1052.03   -43.2 1182.03   -46.1
 1262.03   -44.2 1392.03   -40.2 1432.03   -22.4 1482.03   -10.9 1601.03     -.2
  1739.4     2.9 1768.95    11.3  1781.9    14.9 1800.39    17.9 1806.01    18.5
 1856.27    20.3 1899.43    19.3 1929.21    20.4 2027.93    20.1 2055.71    21.2
#Mann= 3 ,-1 , 0
       0     .06       0  315.03    .025       0 1768.95     .06       0
Bank Sta=315.03,1768.95
XS Rating Curve= 0
Exp/Cntr=.3,.1

Type RM Length L Ch R = 1 ,6352.6  ,1700,1900.8,2240
#Sta/Elev= 30
       0    11.4   23.15    12.3  139.26    12.7   220.6      16  303.72      16
  376.02      18  413.26    15.9  627.51    15.6  833.51    15.9  899.14    11.9
  926.48    11.7 1262.41    11.8 1281.98    10.4 1301.54     3.9 1319.67     2.7
    1340      .6    1680    -4.2    2040   -29.4    2310   -44.4    2470     -43
    2530   -36.6    2650   -20.5    2810      -9 2836.67       2    2884       3
 2901.15    11.7 2914.13    16.2 2937.87    20.2 2956.96    21.4 3010.55    21.8
#Mann= 4 ,-1 , 0
       0     .12       0  627.51     .08       0 1319.67    .025       0
 2937.87     .08       0
Bank Sta=1319.67,2937.87
XS Rating Curve= 0
Exp/Cntr=.3,.1

Type RM Length L Ch R = 1 ,4451.8  ,1440,1267.2,1100
#Sta/Elev= 21
 -357.5214.94085 -217.5210.06223 -132.594.945562       0    -1.3   22.25    -1.1
  700.83    -1.1     860    -2.9     940   -12.1    1030   -27.7    1300   -40.3
    1400   -36.3    1520    -6.3    1700      .1 1702.46     2.8 1711.79     4.9
  1752.8     5.8 1780.31     5.9 1793.12     6.1 1852.75     5.7 1885.51     5.8
 1931.98     5.7
#Mann= 3 ,-1 , 0
 -357.52     .06       0 -132.59    .025       0 1711.79     .07       0
Bank Sta=-132.59,1711.79
XS Rating Curve= 0
Exp/Cntr=.3,.1

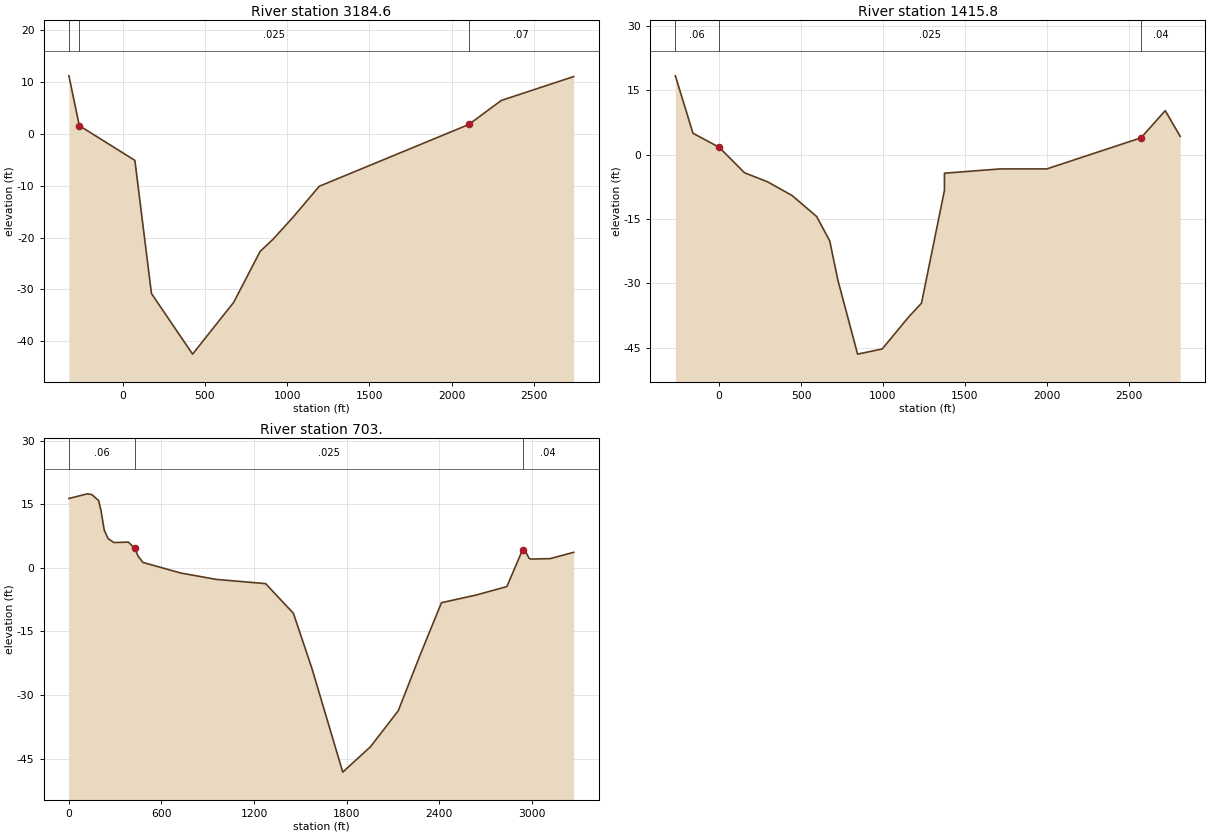
Type RM Length L Ch R = 1 ,3184.6  ,1800,1768.8,1800
#Sta/Elev= 13
 -326.83   11.22 -263.51   1.597   74.28    -5.1     175   -30.8     425   -42.5
     675   -32.5     835   -22.7     915   -20.3    1035   -16.1    1195   -10.1
 2104.33   1.827 2301.55   6.465 2741.87  11.078
#Mann= 3 ,-1 , 0
 -326.83     .06       0 -263.51    .025       0 2104.33     .07       0
Bank Sta=-263.51,2104.33
XS Rating Curve= 0
Exp/Cntr=.3,.1

Type RM Length L Ch R = 1 ,1415.8  ,680,712.8,800
#Sta/Elev= 21
  -266.7  18.412 -159.22   5.018       0    1.76   155.5    -4.2   295.5    -6.3
   445.5    -9.5   595.5   -14.4   675.5   -20.1   725.5   -29.3   845.5   -46.5
   995.5   -45.3  1155.5   -37.9  1235.5   -34.6  1375.5    -8.3  1375.5    -4.3
  1715.5    -3.3  1716.5    -3.3    2000    -3.3    2575    3.95    2723   10.29
  2814.1   4.297
#Mann= 3 ,-1 , 0
  -266.7     .06       0       0    .025       0    2575     .04       0
Bank Sta=0,2575
XS Rating Curve= 0
Exp/Cntr=.3,.1

Type RM Length L Ch R = 1 ,703.    ,703,703,703
#Sta/Elev= 30
       0    16.4  120.06    17.5  150.02    17.3  192.81    15.9  207.81    13.6
  229.32     8.9  254.59     6.9  291.57       6  385.43     6.1  428.82     4.6
  448.17     2.8   480.5     1.3   725.5    -1.2   955.5    -2.7  1275.5    -3.7
  1455.5   -10.7  1575.5   -23.7  1775.5   -48.2  1955.5   -42.2  2135.5   -33.7
  2275.5   -20.7  2415.5    -8.2  2639.5    -6.4  2839.5    -4.4 2941.53     4.3
 2956.33     4.2    2983     2.3 2995.34     2.1 3120.14     2.2  3272.9     3.7
#Mann= 3 , 0 , 0
       0     .06       0  428.82    .025       0 2941.53     .04       0
Bank Sta=428.82,2941.53
XS Rating Curve= 0
Exp/Cntr=.3,.1

Chan Stop Cuts=-1

--- G100-00-00.g02 (geometry) ---

Geom Title= G100-00-00 June 2007 (Floodway)
Program Version=3.10

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
River Reach=G100-00-00      ,G100-00-00_0007

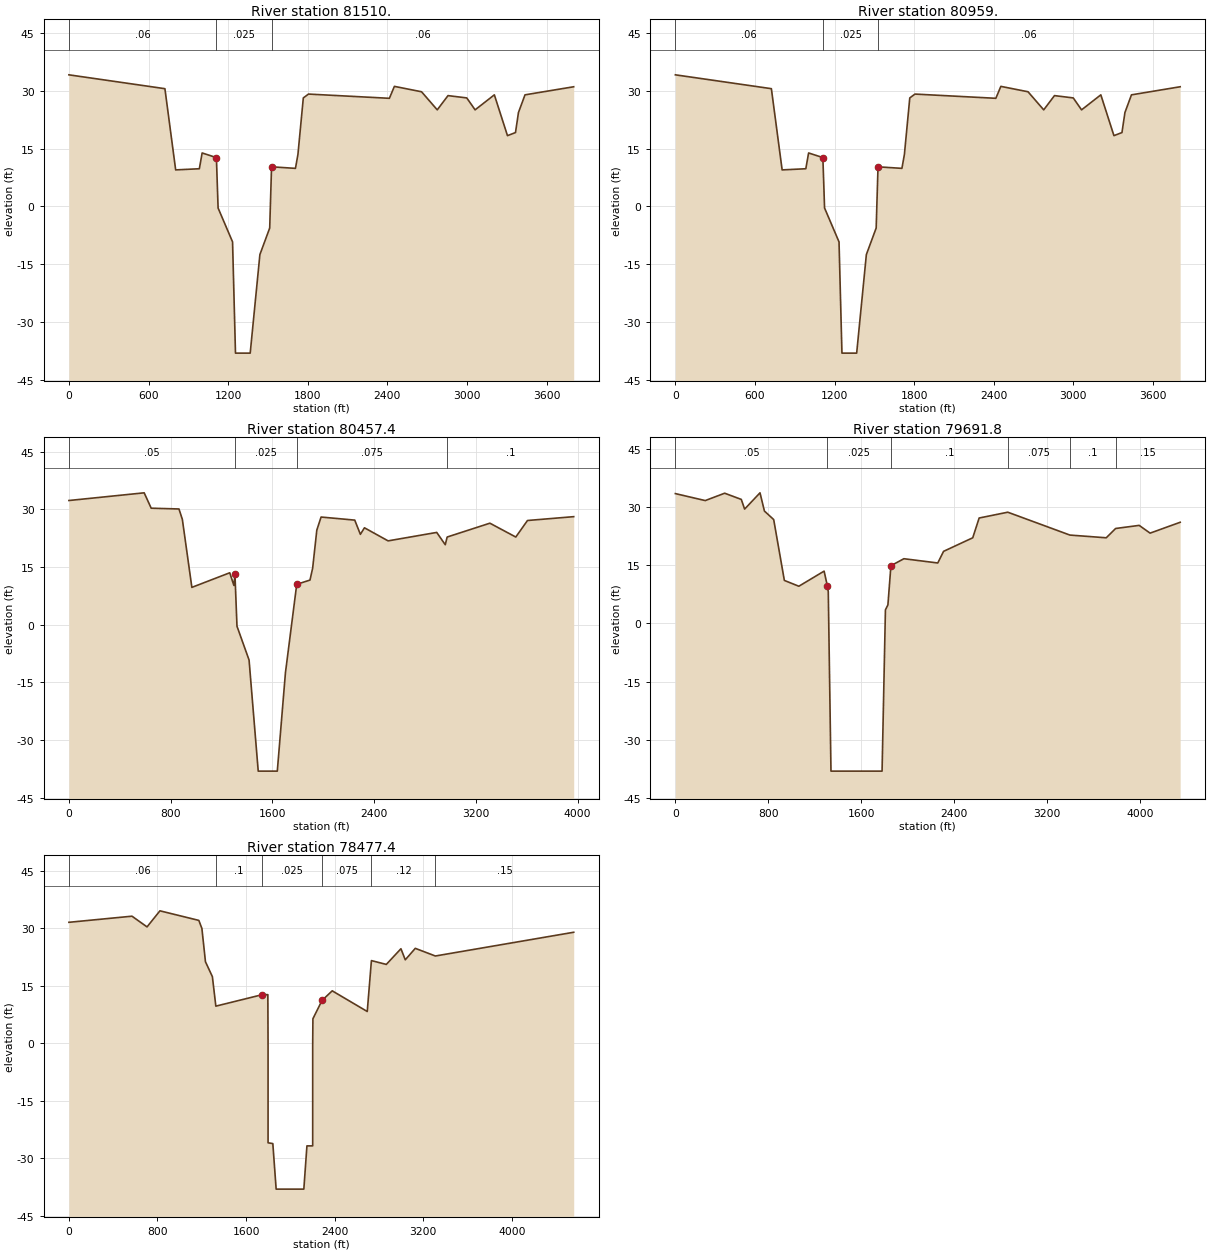
Type RM Length L Ch R = 1 ,81510.  ,551,551,551
BEGIN DESCRIPTION:
Added cross section to match the upper limit of the existing study
END DESCRIPTION:
#Sta/Elev= 30
       0    34.2   723.6    30.6  804.73     9.5   983.2     9.8 1004.22    13.9
 1111.71    12.7  1124.5     -.4  1233.5    -9.2  1255.5   -38.1  1366.5   -38.1
  1439.5   -12.5  1513.5    -5.6 1527.38    10.3 1707.51     9.9 1726.19    13.5
 1766.81    28.2 1805.86    29.2 2415.44    28.1 2453.33    31.2 2657.97    29.8
 2776.26    25.1 2857.44    28.8 2998.82    28.2 3061.61    25.1  3206.7      29
 3305.59    18.4 3366.03    19.2 3388.41    24.4 3437.68      29  3804.8    31.1
#Mann= 3 ,-1 , 0
       0     .06       0 1111.71    .025       0 1527.38     .06       0
#Block Obstruct= 2 , 0
         1007.93   13.87
Bank Sta=1111.71,1527.38
XS Rating Curve= 0
Exp/Cntr=0.3,0.1

Type RM Length L Ch R = 1 ,80959.  ,160,501.6,580
#Sta/Elev= 30
       0    34.2   723.6    30.6  804.73     9.5   983.2     9.8 1004.22    13.9
 1111.71    12.7  1124.5     -.4  1233.5    -9.2  1255.5   -38.1  1366.5   -38.1
  1439.5   -12.5  1513.5    -5.6 1527.38    10.3 1707.51     9.9 1726.19    13.5
 1766.81    28.2 1805.86    29.2 2415.44    28.1 2453.33    31.2 2657.97    29.8
 2776.26    25.1 2857.44    28.8 2998.82    28.2 3061.61    25.1  3206.7      29
 3305.59    18.4 3366.03    19.2 3388.41    24.4 3437.68      29  3804.8    31.1
#Mann= 3 ,-1 , 0
       0     .06       0 1111.71    .025       0 1527.38     .06       0
#Block Obstruct= 2 , 0
         1011.45   13.87
Bank Sta=1111.71,1527.38
XS Rating Curve= 0
Exp/Cntr=0.3,0.1

Type RM Length L Ch R = 1 ,80457.4 ,1600,765.6,480
#Sta/Elev= 30
       0    32.3  591.78    34.3  647.08    30.3   865.3    30.1  891.91    27.4
  966.72     9.7 1264.57    13.5 1297.39    10.2  1305.5    13.1  1321.5     -.4
  1416.5    -9.2  1488.5   -38.1  1638.5   -38.1  1702.5   -12.5 1791.29    10.5
 1895.43    11.6 1916.38    14.7 1949.15    24.6 1982.73      28 2247.35    27.2
 2291.65    23.5 2323.75    25.2 2509.68    21.8 2891.91      24    2959    20.8
 2973.94    22.8 3309.84    26.4 3513.53    22.8 3605.49    27.1 3968.92    28.1
#Mann= 4 ,-1 , 0
       0     .05       0  1305.5    .025       0 1791.29    .075       0
 2973.94      .1       0
Bank Sta=1305.5,1791.29
XS Rating Curve= 0
Exp/Cntr=0.3,0.1

Type RM Length L Ch R = 1 ,79691.8 ,4800,1214.4,640
#Sta/Elev= 30
       0    33.5  257.18    31.7  424.53    33.6  567.77      32  596.32    29.5
  728.79    33.7  766.92      29  846.74    26.8  938.61    11.1 1063.41     9.6
 1280.89    13.5 1309.45     9.6 1316.76     8.2    1340   -38.1    1780   -38.1
 1808.95     3.5 1830.37     4.8 1856.28    14.9 1968.11    16.7 2259.72    15.6
 2309.52    18.6 2560.84    22.1 2616.01    27.2 2862.54    28.7 3397.74    22.8
 3710.54    22.1 3791.39    24.5 3994.12    25.3 4088.21    23.3 4347.18    26.1
#Mann= 6 ,-1 , 0
       0     .05       0 1309.45    .025       0 1856.28      .1       0
 2862.54    .075       0 3397.74      .1       0 3791.39     .15       0
Bank Sta=1309.45,1856.28
XS Rating Curve= 0
Exp/Cntr=0.3,0.1

Type RM Length L Ch R = 1 ,78477.4 ,2160,2296.8,2200
#Sta/Elev= 30
       0    31.6  569.62    33.2  705.58    30.4  822.04    34.6 1173.29    32.1
    1201      30 1233.09    21.3 1295.67    17.4 1326.87     9.7  1746.5    12.7
  1796.5    12.7  1798.5     -.5  1798.5     -26  1841.5   -26.2  1871.5   -38.1
  2121.5   -38.1  2149.5   -26.8  2201.5   -26.8  2201.5     -.5  2203.5     6.4
 2285.96    11.2 2377.89    13.7 2694.19     8.3 2731.79    21.6 2866.42    20.6
 2998.41    24.7 3037.48    21.8 3128.05    24.8 3309.19    22.8 4558.57      29
#Mann= 6 ,-1 , 0
       0     .06       0 1326.87      .1       0  1746.5    .025       0
 2285.96    .075       0 2731.79     .12       0 3309.19     .15       0
#Block Obstruct= 2 , 0
                         2566.96            9.82
Bank Sta=1746.5,2285.96
XS Rating Curve= 0
Exp/Cntr=0.3,0.1